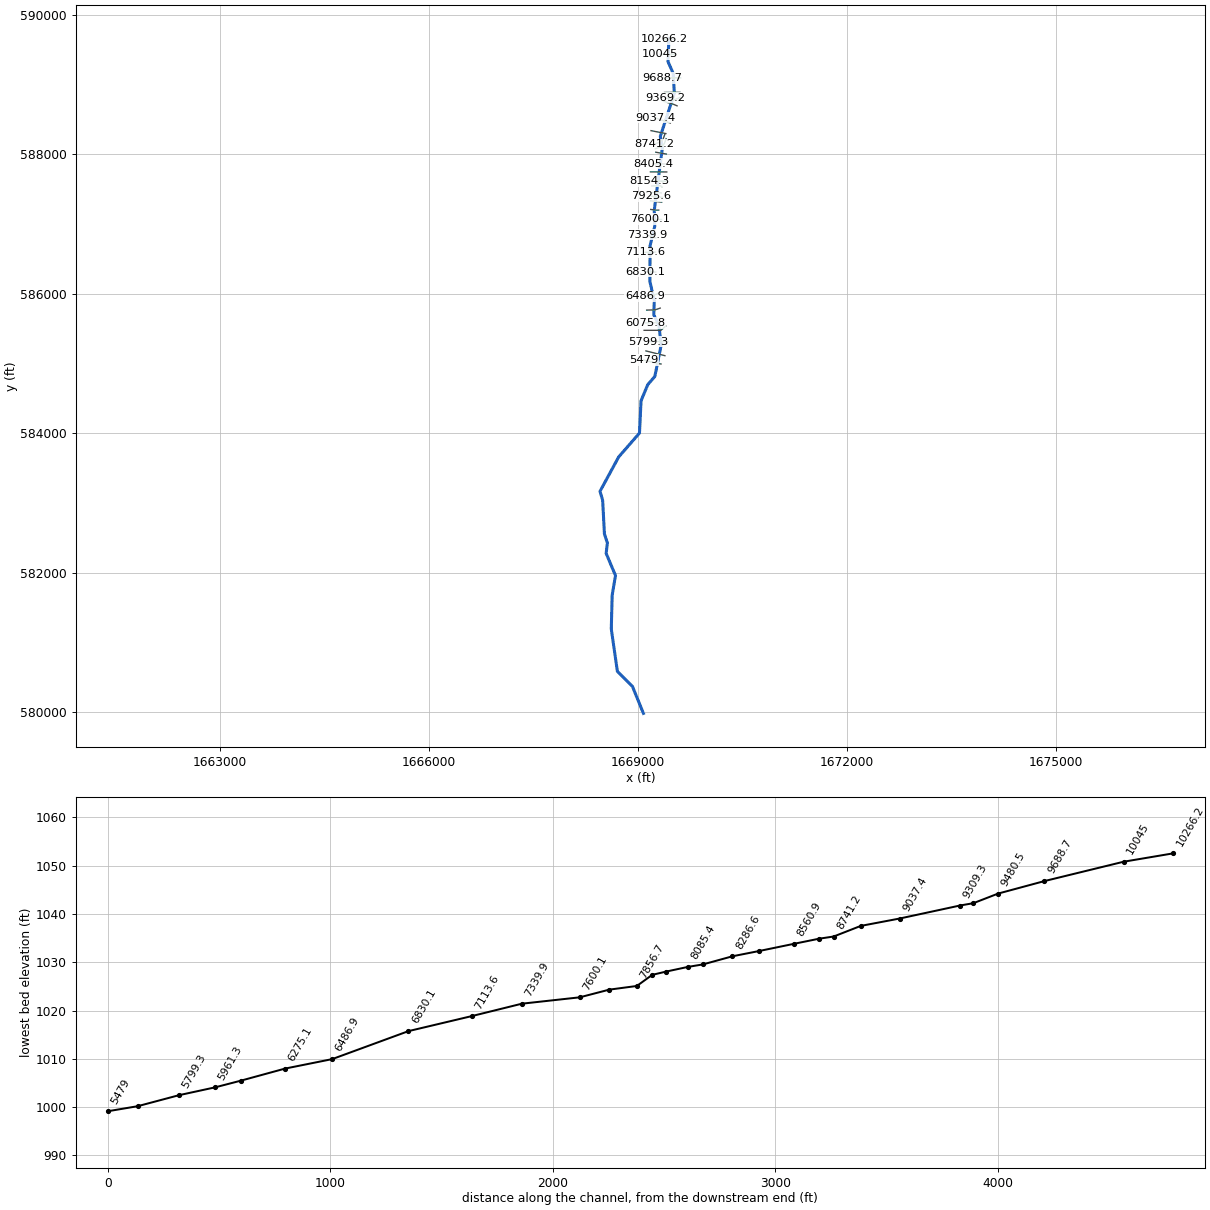
--- MCGRAWRUN.prj (project) ---

Proj Title=MCGRAWRUN
Current Plan=p01
Default Exp/Contr=0,0
English Units
Geom File=g01
Flow File=f01
Plan File=p01
BEGIN DESCRIPTION:
END DESCRIPTION:
DSS Export Rating Curves= 0
DSS Export Rating Curve Sorted= 0
DSS Export Volume Flow Curves= 0
DXF OffsetX= 0
DXF OffsetY= 0
DXF ScaleX= 0
DXF ScaleY= 0

--- MCGRAWRUN.p01 (plan) ---

Plan Title=Floodplain
Program Version=4.00
Geom File=g01
Flow File=f01
K Sum by GR=0
Std Step Tol=0.01
Critical Tol=0.01
Num of Std Step Trials=20
Max Error Tol=0.3
Flow Tol Ratio=0.001
Split Flow NTrial=30
Split Flow Tol=0.02
Split Flow Ratio=0.02
Log Output Level=0
Friction Slope Method=1
Unsteady Friction Slope Method=2
Unsteady Bridges Friction Slope Method=1
Global Log Level=0
CheckData=False
Run HTab=0
Run UNet=0
Run PostProcess=0
UNET Theta=0
UNET Theta Warmup=0
UNET ZTol=0
UNET ZSATol=0
UNET MxIter=0
UNET MaxInSteps=0
UNET DtIC=0
UNET DtMin=0
UNET MaxCRTS=0
UNET WFStab=0
UNET SFStab=0
UNET WFX=0
UNET SFX=0
UNET DSS MLevel=0
UNET DZMax Abort=0
UNET Convert EG Bridges=0
UNET Use Existing IB Tables=0
UNET Froude Limit=0
UNET Froude Power=0
Write IC File=0
Echo Input=False
Echo Output=False
Write Detailed=0

--- MCGRAWRUN.f01 (steady flow) ---

Flow Title=NFF Regression Equation
Program Version=4.00
Number of Profiles=1
Profile Names=P100yr
River Rch & RM=MCGRAWRUN,Main      ,10266.2
889.7776
River Rch & RM=MCGRAWRUN,Main      ,8863.4
959.6110
River Rch & RM=MCGRAWRUN,Main      ,6275.1
1058.086
River Rch & RM=MCGRAWRUN,Main      ,3927.8
1171.688
River Rch & RM=MCGRAWRUN,Main      ,267.9
1230.967
Boundary for River Rch & Prof#=MCGRAWRUN,Main      ,1
Up Type=0
Dn Type=3
Dn Slope=0.018102

--- MCGRAWRUN.g01 (geometry) ---

Geom Title=USGS 10m DEM
Program Version=4.10

River Reach=MCGRAWRUN       ,Main
Reach XY= 30
     1669444.376      589663.089     1669431.356      589330.624
     1669506.008      589159.617     1669522.501      588872.291
     1669321.112      588256.839     1669350.626      588091.909
     1669234.307      587195.207     1669242.119      586970.381
     1669174.887      586690.103     1669171.807      586177.846
     1669235.175      585903.541     1669227.362      585701.284
     1669302.015      585545.902     1669333.265       585265.52
     1669243.485      584818.127     1669141.054       584698.52
     1669045.071      584467.777     1669022.501      584005.103
      1668723.89      583662.221     1668456.375      583169.657
     1668494.353      583040.533     1668519.897      582558.923
     1668562.432      582429.582     1668544.203      582280.277
     1668678.751      581963.437     1668631.008      581682.187
      1668618.05      581198.086     1668705.661      580589.305
     1668921.807      580373.159     1669078.925      579986.874

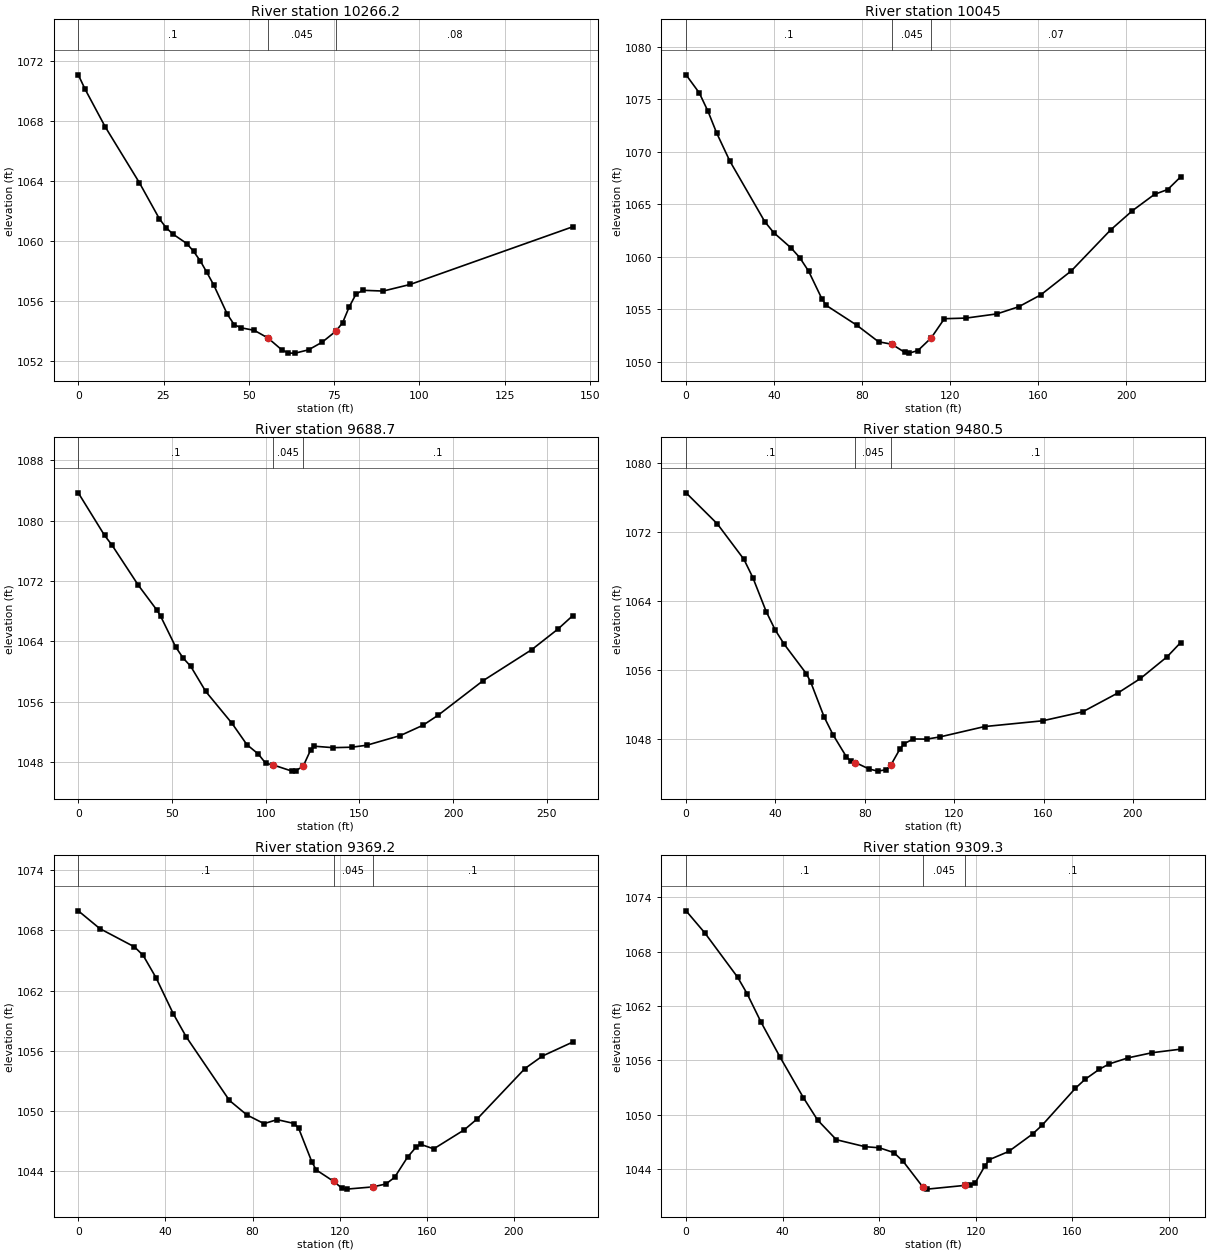
Type RM Length L Ch R = 1 ,10266.2 ,221,221.2,220.3
XS GIS Cut Line= 2
     1669517.799      589653.975     1669372.834      589651.371
#Sta/Elev= 30
       0 1071.11       2 1070.15     7.9 1067.64    17.9 1063.92    23.8  1061.5
    25.8  1060.9    27.8 1060.48    31.8 1059.86    33.8 1059.34    35.8 1058.69
    37.7 1057.93    39.7  1057.1    43.7 1055.14    45.7 1054.45    47.7 1054.24
    51.6 1054.07    55.6 1053.56    59.6 1052.78    61.6 1052.55    63.6 1052.55
    67.5 1052.77    71.5 1053.28    75.5 1054.01    77.5 1054.58    79.4 1055.62
    81.4 1056.48    83.4 1056.74    89.4 1056.69    97.3 1057.13     145 1060.98
#Mann= 3 , 0 , 0
       0      .1       0    55.6    .045       0    75.5     .08       0
Bank Sta=55.6,75.5
XS Rating Curve= 0 ,0
Exp/Cntr=0.3,0.1

Type RM Length L Ch R = 1 ,10045   ,355.7,356.2,356.1
XS GIS Cut Line= 2
     1669544.709      589434.357     1669319.883      589435.225
#Sta/Elev= 30
       0 1077.35       6 1075.63      10 1073.86    13.9 1071.81    19.9 1069.13
    35.8 1063.35    39.8 1062.32    47.8 1060.84    51.7 1059.92    55.7 1058.64
    61.7 1056.02    63.7 1055.38    77.6 1053.49    87.5 1051.91    93.5 1051.68
    99.5 1050.89   101.5 1050.83   105.4 1051.08   111.4 1052.28   117.4 1054.11
   127.3 1054.17   141.3 1054.57   151.2 1055.25   161.2 1056.38   175.1 1058.67
     193 1062.58   202.9 1064.41   212.9 1065.96   218.9 1066.42   224.8 1067.63
#Mann= 3 , 0 , 0
       0      .1       0    93.5    .045       0   111.4     .07       0
Bank Sta=93.5,111.4
XS Rating Curve= 0 ,0
Exp/Cntr=0.3,0.1

Type RM Length L Ch R = 1 ,9688.7  ,207.8,208.3,208.2
XS GIS Cut Line= 2
     1669614.588      589096.032     1669350.699      589095.164
#Sta/Elev= 30
       0  1083.7      14 1078.07      18 1076.77      32 1071.47      42 1068.14
      44 1067.32      52 1063.26      56 1061.79      60 1060.71      68 1057.38
      82 1053.16      90 1050.32      96  1049.1     100 1047.86     104 1047.64
     114 1046.82     116 1046.87     120 1047.47     124 1049.64     126 1050.12
   135.9 1049.93   145.9 1049.99   153.9 1050.25   171.9 1051.54   183.9  1052.9
   191.9 1054.21   215.9 1058.79   241.9 1062.91   255.9 1065.64   263.9 1067.44
#Mann= 3 , 0 , 0
       0      .1       0     104    .045       0     120      .1       0
Bank Sta=104,120
XS Rating Curve= 0 ,0
Exp/Cntr=0.3,0.1

Type RM Length L Ch R = 1 ,9480.5  ,117.1,111.3,105.3
XS GIS Cut Line= 2
     1669602.869      588890.086     1669381.515      588887.482
#Sta/Elev= 30
       0 1076.58      14 1072.97    25.9 1068.85    29.9 1066.72    35.9 1062.76
    39.9 1060.64    43.9 1058.99    53.8 1055.57    55.8 1054.58    61.8 1050.53
    65.8 1048.45    71.8 1045.88    73.8 1045.37    75.8 1045.23    81.8 1044.49
    85.8 1044.23    89.7  1044.4    91.7 1044.95    95.7 1046.79    97.7 1047.43
   101.7 1047.97   107.7 1047.95   113.7 1048.21   133.6 1049.41   159.6 1050.08
   177.5 1051.12   193.4 1053.33   203.4    1055   215.4 1057.54   221.4 1059.18
#Mann= 3 , 0 , 0
       0      .1       0    75.8    .045       0    91.7      .1       0
Bank Sta=75.8,91.7
XS Rating Curve= 0 ,0
Exp/Cntr=0.3,0.1

Type RM Length L Ch R = 1 ,9369.2  ,60.5,59.9,58.8
XS GIS Cut Line= 3
     1669606.341      588816.301     1669516.931      588778.107
     1669391.063      588810.225
#Sta/Elev= 30
       0 1069.95     9.9 1068.18    25.8 1066.36    29.8 1065.51    35.7 1063.29
    43.6 1059.71    49.6 1057.39    69.4 1051.07    77.4 1049.63    85.3 1048.76
    91.3 1049.16    99.2 1048.77   101.2 1048.29   107.2 1044.98   109.2 1044.16
   117.2 1043.02   121.2 1042.31   123.2 1042.24   135.2 1042.46   141.2 1042.75
   145.2  1043.4   151.2 1045.43   155.2 1046.45   157.2  1046.7   163.2 1046.25
   177.2 1048.14   183.2 1049.24   205.1 1054.25   213.1 1055.49   227.1 1056.89
#Mann= 3 , 0 , 0
       0      .1       0   117.2    .045       0   135.2      .1       0
Bank Sta=117.2,135.2
XS Rating Curve= 0 ,0
Exp/Cntr=0.3,0.1

Type RM Length L Ch R = 1 ,9309.3  ,272.4,271.8,270.5
XS GIS Cut Line= 3
      1669562.07      588695.641     1669506.515      588719.079
     1669367.626      588759.878
#Sta/Elev= 30
       0 1072.52     7.8 1070.07    21.4 1065.17    25.3 1063.36    31.1  1060.2
    38.9 1056.38    48.6 1051.88    54.5  1049.4    62.3 1047.22    74.2 1046.45
    80.1 1046.33    86.1  1045.8      90 1044.82      98 1042.04     100 1041.76
   115.8 1042.18   117.8 1042.18   119.8 1042.44   123.8  1044.3   125.7 1045.02
   133.7 1045.92   143.6 1047.85   147.6 1048.83   161.4 1052.92   165.4  1053.9
   171.3 1055.01   175.3 1055.59   183.2 1056.27   193.2 1056.84     205 1057.23
#Mann= 3 , 0 , 0
       0      .1       0      98    .045       0   115.8      .1       0
Bank Sta=98,115.8
XS Rating Curve= 0 ,0
Exp/Cntr=0.3,0.1

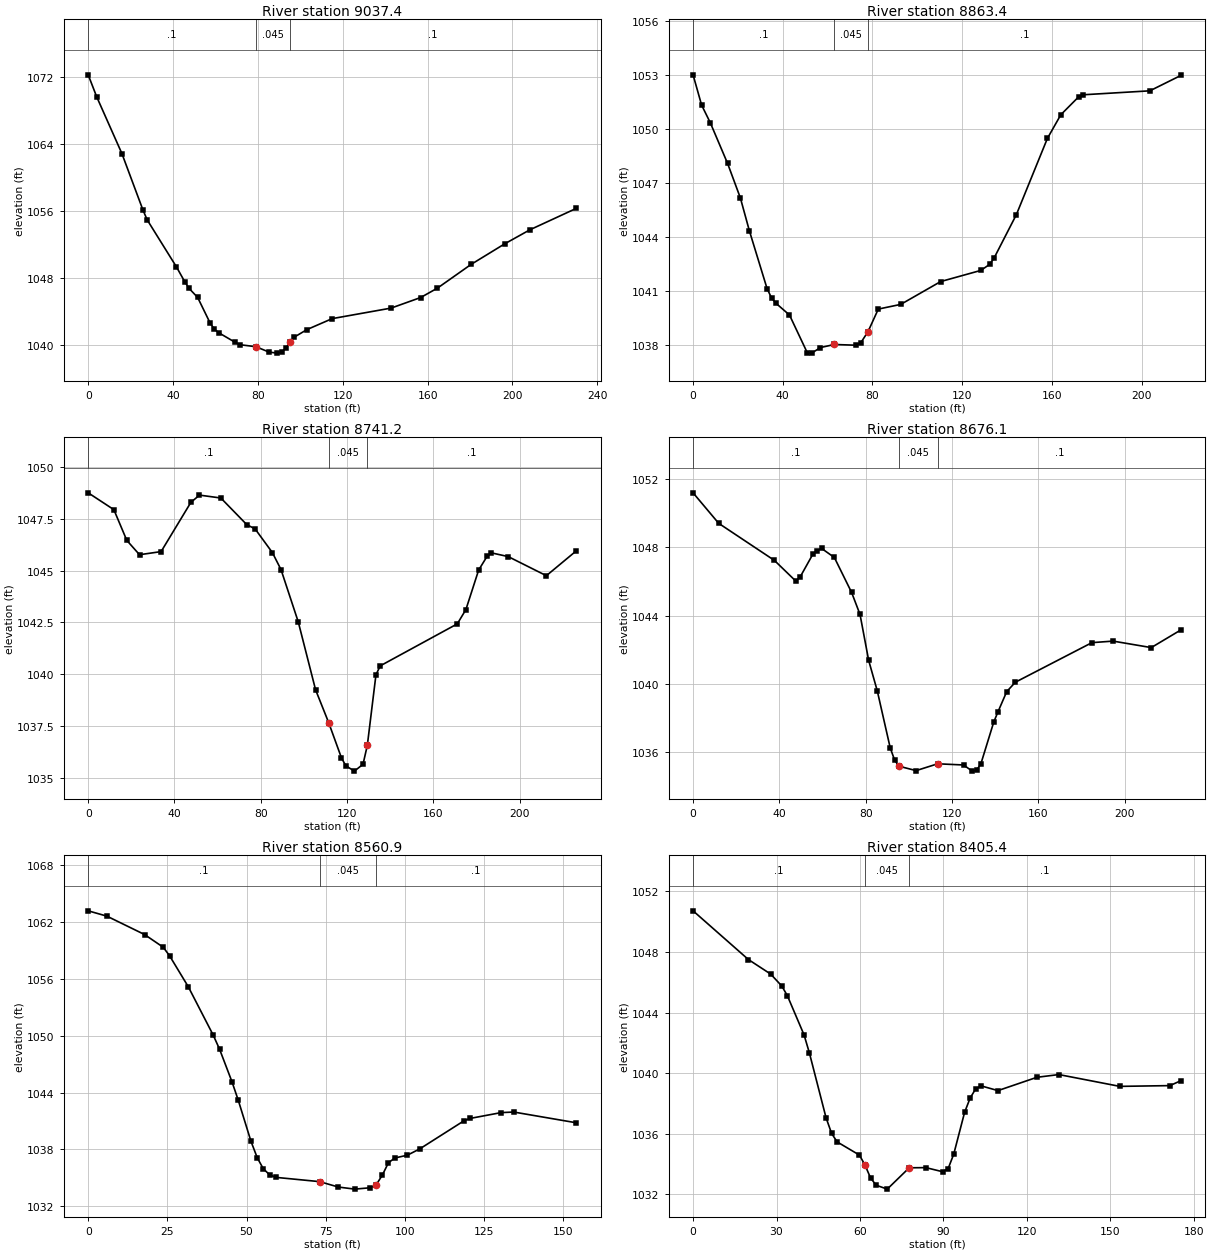
Type RM Length L Ch R = 1 ,9037.4  ,171.1,174.1,177
XS GIS Cut Line= 2
     1669465.716      588449.114     1669247.834      588522.898
#Sta/Elev= 30
       0  1072.3       4 1069.68    15.9 1062.89    25.8 1056.16    27.8 1054.98
    41.6 1049.36    45.6 1047.55    47.6 1046.78    51.6 1045.71    57.5 1042.64
    59.5 1041.91    61.5  1041.5    69.4 1040.33    71.4 1040.07      79 1039.83
    85.3 1039.18    89.2 1039.06    91.2  1039.2    93.2 1039.66    95.2 1040.41
    97.2 1040.98   103.1 1041.87     115 1043.18   142.8 1044.44   156.7  1045.7
   164.6 1046.82   180.5 1049.66   196.3 1052.11   208.2 1053.79     230 1056.34
#Mann= 3 , 0 , 0
       0      .1       0      79    .045       0    95.2      .1       0
Bank Sta=79,95.2
XS Rating Curve= 0 ,0
Exp/Cntr=0.3,0.1

Type RM Length L Ch R = 1 ,8863.4  ,102.2,122.1,141.3
XS GIS Cut Line= 3
      1669401.48      588298.072     1669380.647      588301.544
     1669187.938      588339.739
#Sta/Elev= 30
       0 1053.02     3.8 1051.34     7.7 1050.35    15.4 1048.09    21.1 1046.17
    25.1 1044.35      33 1041.13      35 1040.61      37 1040.31      43 1039.66
    50.9 1037.57    52.9 1037.54    56.8 1037.85      63 1038.02    72.7 1037.98
    74.7  1038.1      78 1038.73    82.6 1039.99    92.6 1040.25   110.4 1041.52
   128.3 1042.14   132.2 1042.47   134.2 1042.82   144.2 1045.25     158 1049.48
     164  1050.8   171.9 1051.79   173.9 1051.91   203.7 1052.13   217.6 1052.99
#Mann= 3 , 0 , 0
       0      .1       0      63    .045       0      78      .1       0
Bank Sta=63,78
XS Rating Curve= 0 ,0
Exp/Cntr=0.3,0.1

Type RM Length L Ch R = 1 ,8741.2  ,65.1,65.1,67.6
XS GIS Cut Line= 4
     1669386.723      588289.391     1669360.681      588216.475
     1669299.049      588168.732     1669232.209      588145.294
#Sta/Elev= 30
       0 1048.74    11.9 1047.93    17.9 1046.45    23.8 1045.76    33.8 1045.91
    47.6 1048.28    51.6 1048.63    61.5 1048.49    73.5 1047.21    77.4    1047
    85.4 1045.86    89.4 1045.04    97.4 1042.52   105.4 1039.26   111.5 1037.67
   117.4 1035.98   119.4  1035.6   123.4 1035.34   127.4 1035.67   129.4 1036.58
   133.4 1039.98   135.4 1040.41   171.1 1042.43   175.1 1043.12     181 1045.02
   184.9 1045.68   186.9 1045.85   194.7 1045.67   212.4 1044.75   226.2 1045.94
#Mann= 3 , 0 , 0
       0      .1       0   111.5    .045       0   129.4      .1       0
Bank Sta=111.5,129.4
XS Rating Curve= 0 ,0
Exp/Cntr=0.3,0.1

Type RM Length L Ch R = 1 ,8676.1  ,134.1,115.2,93.8
XS GIS Cut Line= 4
     1669404.084      588224.287     1669378.042      588151.371
     1669316.411      588103.628      1669249.57       588080.19
#Sta/Elev= 30
       0  1051.2    11.9 1049.41    37.7 1047.24    47.6 1046.03    49.6 1046.26
    55.6 1047.62    57.6 1047.82    59.6 1047.94    65.5 1047.41    73.5 1045.36
    77.4 1044.07    81.4 1041.38    85.4 1039.59    91.4 1036.25    93.4 1035.55
    95.4 1035.18   103.4 1034.92   113.4 1035.32   125.4 1035.25   129.4 1034.89
   131.4 1034.94   133.4 1035.31   139.4 1037.77   141.4 1038.38   145.4 1039.55
   149.4  1040.1   184.9 1042.42   194.7 1042.51   212.4 1042.13   226.2 1043.17
#Mann= 3 , 0 , 0
       0      .1       0    95.4    .045       0   113.4      .1       0
Bank Sta=95.4,113.4
XS Rating Curve= 0 ,0
Exp/Cntr=0.3,0.1

Type RM Length L Ch R = 1 ,8560.9  ,152,155.5,159
XS GIS Cut Line= 2
     1669407.556      588004.669     1669255.647      588030.711
#Sta/Elev= 30
       0 1063.16     5.9  1062.6    17.8 1060.66    23.7 1059.32    25.7 1058.42
    31.6 1055.16    39.5 1050.04    41.5 1048.56    45.4 1045.14    47.4 1043.18
    51.4 1038.86    53.4 1037.11    55.3 1035.96    57.3 1035.32    59.3 1035.05
    73.1  1034.6      79 1034.03    84.2 1033.81    88.9 1033.95    90.9 1034.24
    92.9 1035.29    94.8 1036.58    96.8 1037.09   100.8 1037.39   104.7 1038.05
   118.6    1041   120.5 1041.26   130.4 1041.88   134.4 1041.94   154.1 1040.81
#Mann= 3 , 0 , 0
       0      .1       0    73.1    .045       0    90.9      .1       0
Bank Sta=73.1,90.9
XS Rating Curve= 0 ,0
Exp/Cntr=0.3,0.1

Type RM Length L Ch R = 1 ,8405.4  ,118.2,118.8,118.9
XS GIS Cut Line= 2
     1669391.063      587862.308     1669215.716      587864.912
#Sta/Elev= 30
       0 1050.72    19.9  1047.5    27.9 1046.54    31.9 1045.75    33.9 1045.11
    39.9 1042.52    41.8 1041.34    47.8 1037.05    49.8 1036.01    51.8 1035.45
    59.8 1034.58    61.8 1033.92    63.8 1033.07    65.8 1032.59    69.8 1032.33
    77.7 1033.74    83.7 1033.75    89.7 1033.48    91.7 1033.69    93.7 1034.64
    97.6  1037.4    99.6 1038.35   101.6 1038.96   103.6 1039.15   109.6 1038.84
   123.6 1039.72   131.5  1039.9   153.4 1039.12   171.4 1039.17   175.4  1039.5
#Mann= 3 , 0 , 0
       0      .1       0    61.8    .045       0    77.7      .1       0
Bank Sta=61.8,77.7
XS Rating Curve= 0 ,0
Exp/Cntr=0.3,0.1

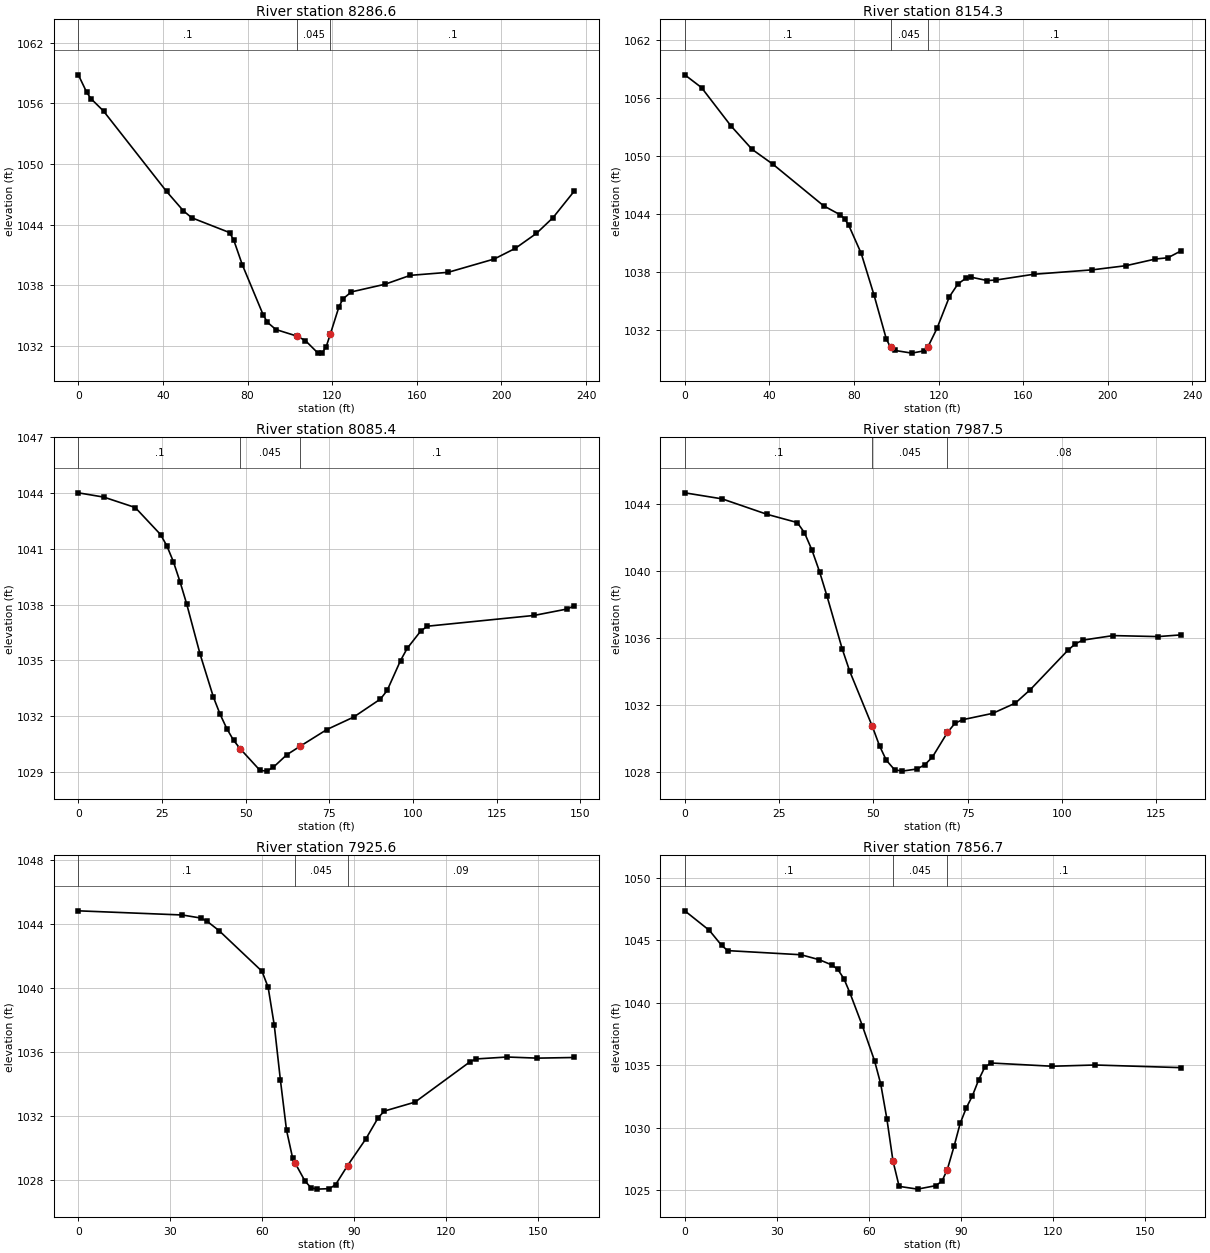
Type RM Length L Ch R = 1 ,8286.6  ,132.3,132.3,132.1
XS GIS Cut Line= 2
     1669413.633      587747.725     1669179.258      587748.593
#Sta/Elev= 30
       0 1058.84       4 1057.09       6 1056.47    11.9 1055.25    41.7 1047.28
    49.7 1045.35    53.6 1044.67    71.5  1043.2    73.5 1042.44    77.5 1040.02
    87.4 1035.04    89.4  1034.3    93.4 1033.59   103.3 1032.94   107.3  1032.5
   113.2 1031.27   115.2 1031.25   117.2  1031.9   119.2 1033.18   123.2 1035.84
   125.1 1036.63   129.1 1037.32     145 1038.08   156.9 1038.96   174.8 1039.26
   196.6 1040.58   206.6 1041.64   216.5 1043.11   224.4 1044.68   234.4  1047.3
#Mann= 3 , 0 , 0
       0      .1       0   103.3    .045       0   119.2      .1       0
Bank Sta=103.3,119.2
XS Rating Curve= 0 ,0
Exp/Cntr=0.3,0.1

Type RM Length L Ch R = 1 ,8154.3  ,68,68.9,69.8
XS GIS Cut Line= 2
     1669404.084      587616.648     1669169.709      587617.516
#Sta/Elev= 30
       0 1058.37     7.9 1057.05    21.8 1053.09    31.8 1050.66    41.7 1049.11
    65.6 1044.82    73.5 1043.88    75.5 1043.48    77.5  1042.8    83.4 1039.89
    89.4 1035.62    95.3 1031.01    97.3 1030.16    99.3 1029.85   107.3 1029.57
   113.2 1029.81     115 1030.24   119.2 1032.12   125.1 1035.41   129.1 1036.72
   133.1 1037.36   135.1 1037.44     143 1037.08     147 1037.13   164.9 1037.73
   192.7 1038.19   208.6 1038.62   222.5 1039.31   228.4 1039.44   234.4 1040.13
#Mann= 3 , 0 , 0
       0      .1       0    97.3    .045       0     115      .1       0
Bank Sta=97.3,115
XS Rating Curve= 0 ,0
Exp/Cntr=0.3,0.1

Type RM Length L Ch R = 1 ,8085.4  ,98.7,97.9,97.1
XS GIS Cut Line= 3
      1669343.32      587538.523     1669317.279      587549.808
     1669197.487      587547.204
#Sta/Elev= 30
       0 1044.02     7.6 1043.79      17 1043.23    24.6 1041.77    26.5 1041.15
    28.4 1040.32    30.4 1039.23    32.4 1038.03    36.4 1035.33    40.4 1033.01
    42.4 1032.09    44.4 1031.32    46.4  1030.7    48.4 1030.24    54.3 1029.08
    56.3 1029.04    58.3 1029.25    62.3 1029.92    66.3 1030.38    74.3 1031.28
    82.3 1031.95    90.3 1032.92    92.3 1033.38    96.3 1034.99    98.3 1035.65
   102.3 1036.57   104.3 1036.84   136.2 1037.42   146.2 1037.77   148.2 1037.94
#Mann= 3 , 0 , 0
       0      .1       0    48.4    .045       0    66.3      .1       0
Bank Sta=48.4,66.3
XS Rating Curve= 0 ,0
Exp/Cntr=0.3,0.1

Type RM Length L Ch R = 1 ,7987.5  ,64.4,61.9,59
XS GIS Cut Line= 3
     1669336.376      587447.378     1669299.049      587452.586
     1669205.299      587452.586
#Sta/Elev= 30
       0 1044.64     9.9 1044.28    21.8 1043.36    29.8 1042.87    31.7 1042.27
    33.7 1041.23    35.7 1039.95    37.7 1038.48    41.7 1035.36    43.7 1034.02
    49.7 1030.73    51.6 1029.58    53.4 1028.72    55.6 1028.15    57.6 1028.07
    61.6  1028.2    63.6 1028.45    65.6  1028.9    69.6 1030.37    71.6 1030.92
    73.6 1031.13    81.6 1031.51    87.6 1032.12    91.6 1032.93   101.5 1035.26
   103.5 1035.65   105.5 1035.87   113.5 1036.14   125.4 1036.08   131.4 1036.18
#Mann= 3 , 0 , 0
       0      .1       0    49.7    .045       0    69.6     .08       0
Bank Sta=49.7,69.6
XS Rating Curve= 0 ,0
Exp/Cntr=0.3,0.1

Type RM Length L Ch R = 1 ,7925.6  ,69.1,68.9,69.1
XS GIS Cut Line= 2
     1669354.605      587382.273     1669194.015      587401.371
#Sta/Elev= 27
       0  1044.8    33.9 1044.54    39.9 1044.35    41.9 1044.16    45.9 1043.56
    59.9 1041.02    61.9 1040.02    63.9 1037.65    65.9 1034.22    67.9 1031.08
    69.9 1029.33    70.7 1029.03    73.9 1027.91    75.9 1027.48    77.9  1027.4
    81.9 1027.43    83.9 1027.68    87.8 1028.87    93.8 1030.55    97.8 1031.87
    99.8 1032.28   109.8 1032.84   127.8 1035.37   129.8 1035.54   139.8 1035.66
   149.7 1035.59   161.7 1035.63
#Mann= 3 , 0 , 0
       0      .1       0    70.7    .045       0    87.8     .09       0
Bank Sta=70.7,87.8
XS Rating Curve= 0 ,0
Exp/Cntr=0.3,0.1

Type RM Length L Ch R = 1 ,7856.7  ,124,124,123.3
XS GIS Cut Line= 2
     1669341.584      587314.565     1669180.994      587333.662
#Sta/Elev= 30
       0 1047.34       8 1045.78      12 1044.58      14 1044.16    37.9 1043.83
    43.9 1043.43    47.9 1043.02    49.9 1042.66    51.9 1041.91    53.9 1040.75
    57.9 1038.16    61.9 1035.34    63.9  1033.5    65.9 1030.72    67.9 1027.34
    69.9 1025.32    75.9  1025.1    81.9 1025.38    83.9 1025.75    85.6 1026.66
    87.8 1028.51    89.8 1030.35    91.8 1031.59    93.8 1032.56    95.8 1033.81
    97.8 1034.83    99.8 1035.18   119.8 1034.92   133.8 1035.02   161.7 1034.81
#Mann= 3 , 0 , 0
       0      .1       0    67.9    .045       0    85.6      .1       0
Bank Sta=67.9,85.6
XS Rating Curve= 0 ,0
Exp/Cntr=0.3,0.1

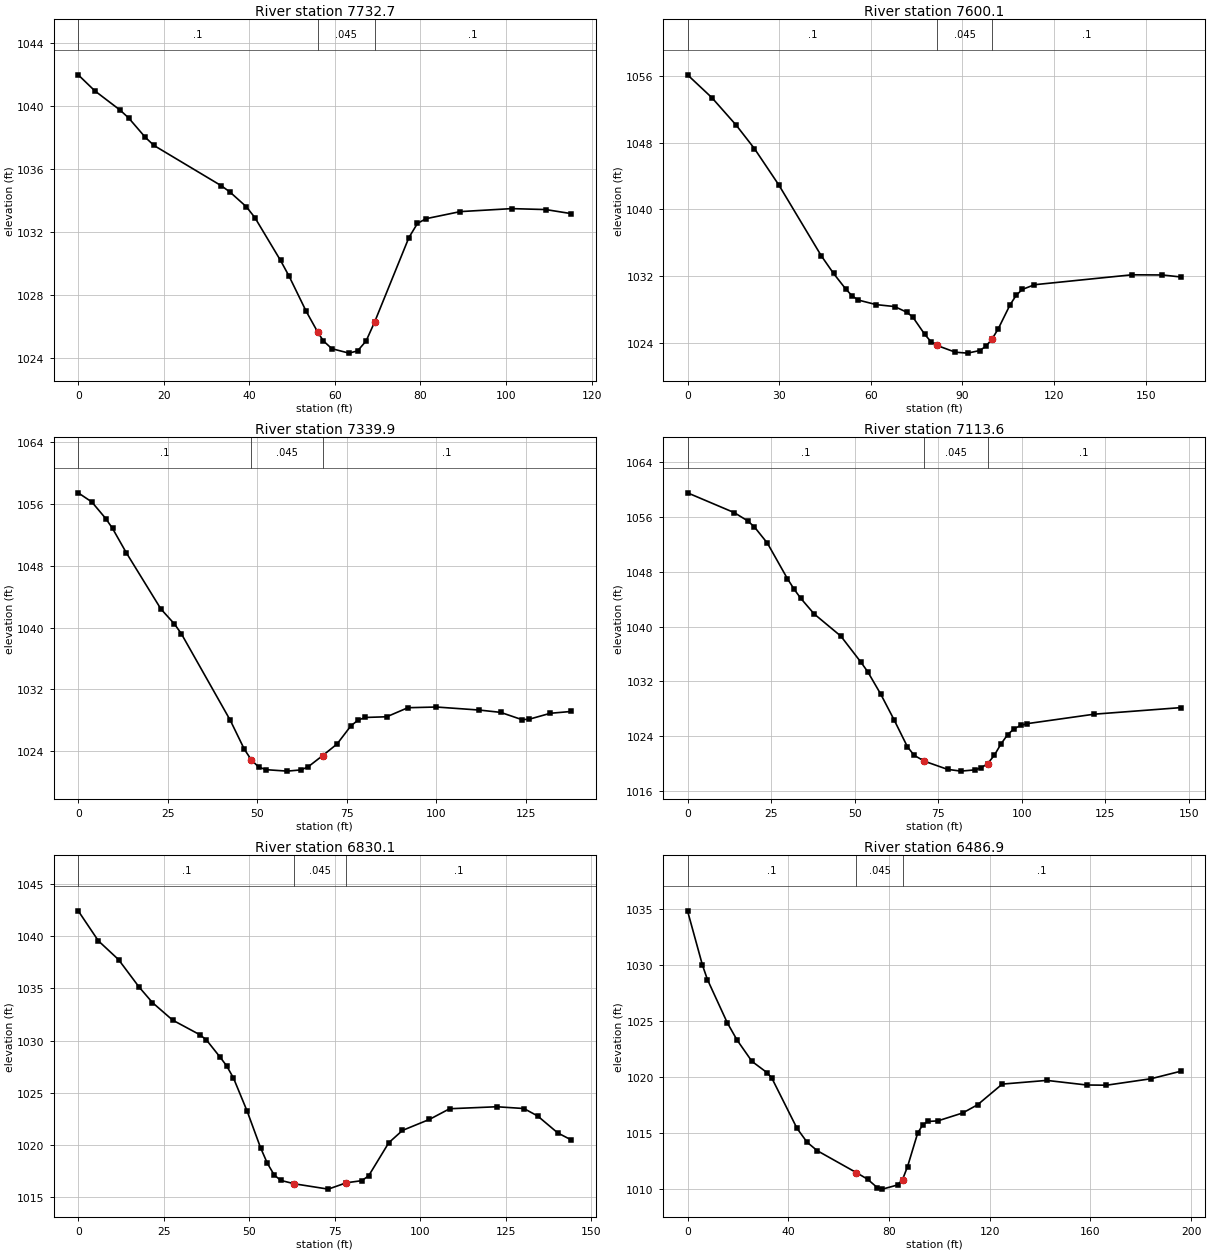
Type RM Length L Ch R = 1 ,7732.7  ,129.3,132.6,135.5
XS GIS Cut Line= 3
     1669299.049       587200.85     1669261.723      587199.982
     1669184.466      587210.398
#Sta/Elev= 27
       0    1042     3.9 1040.98     9.8 1039.76    11.8 1039.26    15.7 1038.03
    17.7 1037.52    33.4 1034.97    35.4 1034.58    39.3 1033.63    41.3 1032.94
    47.3 1030.22    49.3 1029.22    53.3 1026.99      56 1025.67    57.3 1025.12
    59.3 1024.62    63.3 1024.34    65.3 1024.48    67.3 1025.11    69.3 1026.32
    77.3 1031.67    79.3 1032.57    81.3 1032.87    89.3 1033.32   101.3 1033.51
   109.3 1033.45   115.3 1033.19
#Mann= 3 , 0 , 0
       0      .1       0      56    .045       0    69.3      .1       0
Bank Sta=56,69.3
XS Rating Curve= 0 ,0
Exp/Cntr=0.3,0.1

Type RM Length L Ch R = 1 ,7600.1  ,267.8,260.1,252.3
XS GIS Cut Line= 2
     1669333.772      587074.114     1669172.313      587074.114
#Sta/Elev= 30
       0 1056.15       8  1053.4      16 1050.08    21.9  1047.3    29.9 1042.93
    43.8 1034.43    47.8 1032.32    51.8 1030.45    53.8 1029.66    55.8 1029.13
    61.8 1028.57    67.8 1028.34    71.8 1027.66    73.8 1027.06    77.7 1024.99
    79.7 1024.13    81.7 1023.67    87.7 1022.86    91.7 1022.75    95.7 1023.06
    97.7 1023.58    99.7 1024.44   101.7 1025.64   105.6 1028.54   107.6 1029.68
   109.6 1030.39   113.6 1030.96   145.5 1032.15   155.5 1032.13   161.5 1031.89
#Mann= 3 , 0 , 0
       0      .1       0    81.7    .045       0    99.7      .1       0
Bank Sta=81.7,99.7
XS Rating Curve= 0 ,0
Exp/Cntr=0.3,0.1

Type RM Length L Ch R = 1 ,7339.9  ,217.8,226.3,234.2
XS GIS Cut Line= 3
     1669256.515      586801.544     1669221.792      586812.829
     1669126.306      586846.683
#Sta/Elev= 30
       0 1057.42     3.8 1056.24     7.7 1054.09     9.6 1052.81    13.4  1049.7
    23.1  1042.4    26.9 1040.45    28.8 1039.21    42.5 1027.99    46.4 1024.27
    48.4 1022.86    50.4 1021.97    52.4 1021.62    58.4 1021.43    62.3 1021.59
    64.3 1022.01    68.3 1023.44    72.3 1024.93    76.2 1027.29    78.2 1028.03
    80.2 1028.37    86.2 1028.46    92.1 1029.63   100.1 1029.72     112 1029.33
     118 1029.03   123.9  1028.1   125.9 1028.13   131.9 1028.91   137.8 1029.15
#Mann= 3 , 0 , 0
       0      .1       0    48.4    .045       0    68.3      .1       0
Bank Sta=48.4,68.3
XS Rating Curve= 0 ,0
Exp/Cntr=0.3,0.1

Type RM Length L Ch R = 1 ,7113.6  ,284.7,283.5,282.3
XS GIS Cut Line= 2
     1669251.306      586599.287     1669103.737      586595.815
#Sta/Elev= 30
       0 1059.56      14 1056.66      18 1055.46      20 1054.58    23.9  1052.2
    29.9    1047    31.9 1045.46    33.9 1044.12    37.9 1041.84    45.9 1038.59
    51.9 1034.78    53.9 1033.41    57.8 1030.13    61.8 1026.37    65.8 1022.42
    67.8 1021.17    70.9  1020.3    77.8 1019.11    81.8 1018.85    85.9 1019.03
    87.8 1019.31    89.8 1019.94    91.8 1021.16    93.8 1022.82    95.8 1024.19
    97.7 1025.03    99.7 1025.54   101.7  1025.8   121.7 1027.18   147.6 1028.14
#Mann= 3 , 0 , 0
       0      .1       0    70.9    .045       0    89.8      .1       0
Bank Sta=70.9,89.8
XS Rating Curve= 0 ,0
Exp/Cntr=0.3,0.1

Type RM Length L Ch R = 1 ,6830.1  ,334.8,343.2,350.7
XS GIS Cut Line= 2
     1669255.647      586312.829     1669111.549      586317.169
#Sta/Elev= 30
       0 1042.44     5.9 1039.56    11.8 1037.76    17.8 1035.13    21.7 1033.64
    27.6 1031.96    35.6 1030.55    37.5 1030.05    41.5  1028.4    43.4 1027.57
    45.4  1026.4    49.4 1023.22    53.3 1019.73    55.3 1018.23    57.3 1017.11
    59.2 1016.59    63.2 1016.26    73.1 1015.75    78.4 1016.36    82.9 1016.56
    84.9 1017.02    90.8  1020.2    94.8 1021.38   102.7 1022.44   108.6 1023.46
   122.4 1023.65   130.3 1023.48   134.3 1022.77   140.2 1021.14   144.2 1020.46
#Mann= 3 , 0 , 0
       0      .1       0    63.2    .045       0    78.4      .1       0
Bank Sta=63.2,78.4
XS Rating Curve= 0 ,0
Exp/Cntr=0.3,0.1

Type RM Length L Ch R = 1 ,6486.9  ,215.9,211.8,205
XS GIS Cut Line= 4
     1669287.765      586004.669     1669256.515      585992.516
     1669194.015      585971.683     1669097.661      585966.475
#Sta/Elev= 30
       0 1034.83     5.9    1030     7.9 1028.69    15.8 1024.82    19.7 1023.27
    25.6 1021.37    31.6 1020.36    33.5 1019.87    43.5 1015.38    47.5 1014.14
    51.5 1013.39    67.1 1011.42    71.5 1010.84    75.4 1010.08    77.4 1009.95
    83.4 1010.32    85.4 1010.81    87.4 1011.97    91.4 1014.95    93.4 1015.69
    95.4    1016    99.4 1016.05   109.3 1016.76   115.2 1017.49     125 1019.34
   142.7 1019.67   158.5 1019.26   166.4 1019.24   184.1 1019.82   195.9 1020.49
#Mann= 3 , 0 , 0
       0      .1       0    67.1    .045       0    85.4      .1       0
Bank Sta=67.1,85.4
XS Rating Curve= 0 ,0
Exp/Cntr=0.3,0.1

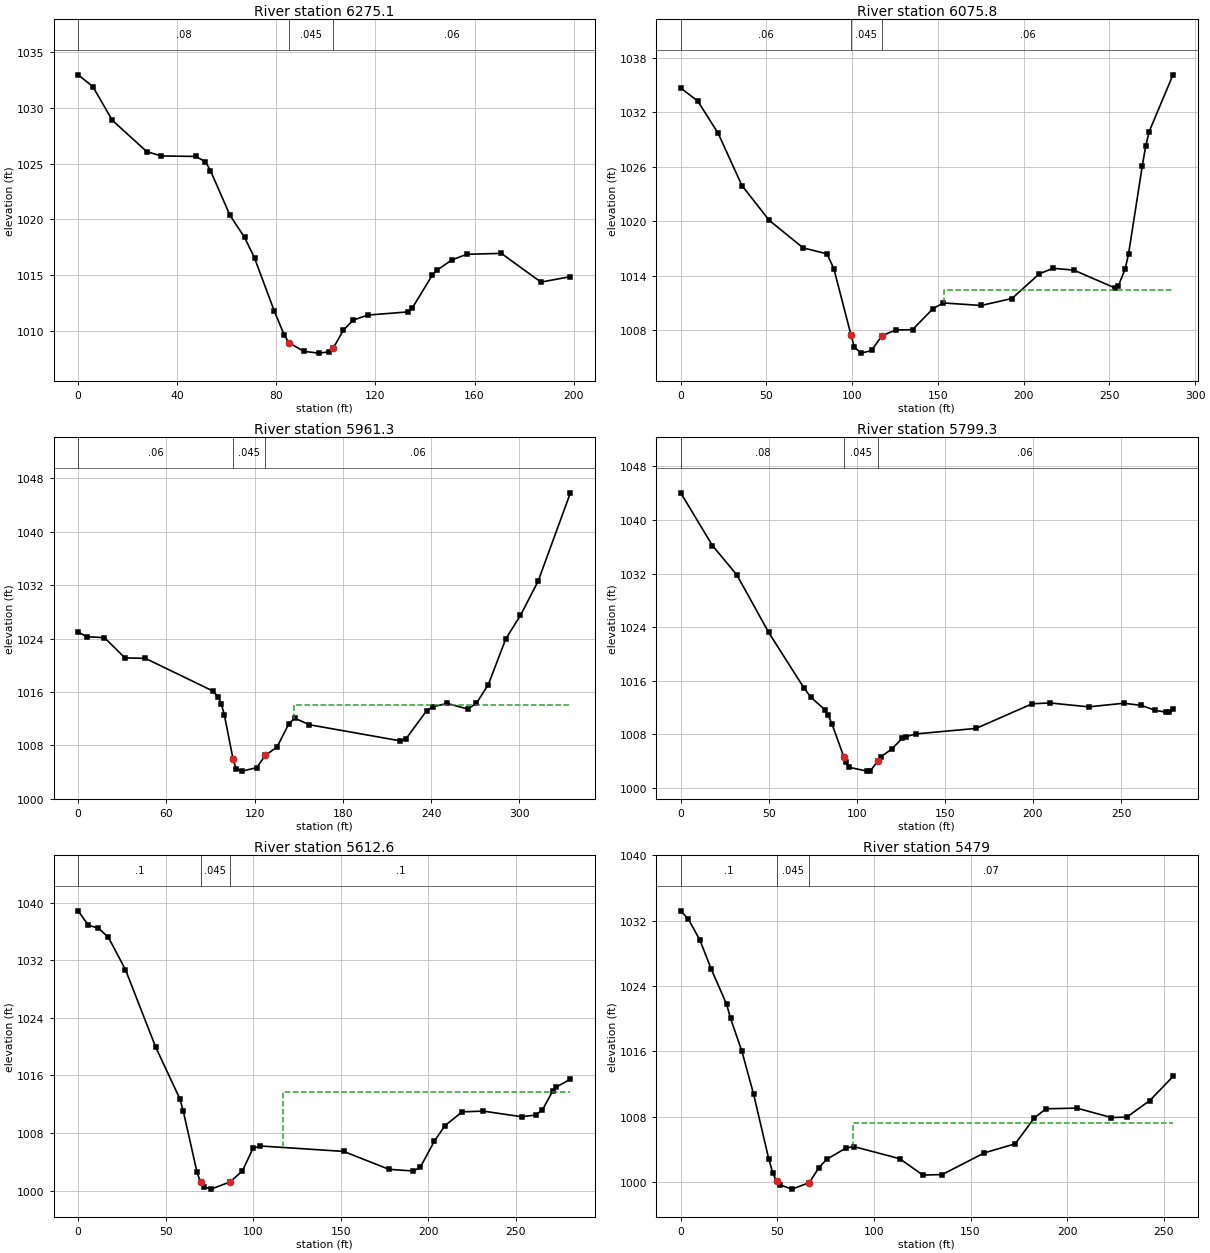
Type RM Length L Ch R = 1 ,6275.1  ,200.7,199.3,198.7
XS GIS Cut Line= 3
     1669319.883      585796.336     1669246.966      585771.162
     1669125.438       585767.69
#Sta/Elev= 30
       0 1032.99     5.9 1031.94    13.8  1028.9    27.7 1026.09    33.6  1025.7
    47.5 1025.66    51.4 1025.17    53.4 1024.39    61.3 1020.36    67.2 1018.38
    71.2 1016.53    79.1 1011.81    83.1 1009.66      85 1008.93    91.1 1008.15
    97.1 1007.99   101.1  1008.1     103 1008.45     107 1010.03     111 1010.96
     117 1011.41     133 1011.69   134.9 1012.05   142.9 1014.98   144.9 1015.45
   150.9 1016.37   156.9 1016.87   170.8 1016.95   186.8 1014.37   198.7 1014.86
#Mann= 3 , 0 , 0
       0     .08       0      85    .045       0     103     .06       0
Bank Sta=85,103
XS Rating Curve= 0 ,0
Exp/Cntr=0.3,0.1

Type RM Length L Ch R = 1 ,6075.8  ,112.6,114.6,113.6
XS GIS Cut Line= 3
     1669380.647      585630.537     1669310.334      585589.739
     1669104.605      585582.794
#Sta/Elev= 30
       0 1034.69     9.9 1033.27    21.8 1029.72    35.7 1023.95    51.6 1020.12
    71.4 1017.08    85.3 1016.42    89.3 1014.79    99.3 1007.49   101.3 1006.12
   105.3 1005.48   111.3 1005.77   117.3  1007.4   125.3 1008.02   135.2 1008.07
   147.2 1010.39   153.2 1011.01   175.2 1010.73   193.2  1011.5   209.2 1014.23
   217.2 1014.83   229.2 1014.63   253.2 1012.67   255.2 1012.86   259.2 1014.76
   261.2 1016.43   269.2 1026.12   271.2  1028.3   273.2 1029.89   287.1 1036.15
#Mann= 3 , 0 , 0
       0     .06       0    99.3    .045       0   117.3     .06       0
#XS Ineff= 2 , 0
                          153.27          1012.4
Permanent Ineff=
       F       F
Bank Sta=99.3,117.3
XS Rating Curve= 0 ,0
Exp/Cntr=0.3,0.1

Type RM Length L Ch R = 1 ,5961.3  ,164,162,161.5
XS GIS Cut Line= 3
     1669399.744      585540.259     1669330.299      585477.759
      1669088.98      585477.759
#Sta/Elev= 30
       0 1024.96       6 1024.27    17.9 1024.13    31.8 1021.09    45.7 1021.03
    91.4 1016.15    95.4 1015.24    97.4 1014.16    99.4 1012.58   105.4 1005.86
   107.4 1004.47   111.4 1004.11   121.4 1004.63   127.3 1006.46   135.3 1007.74
   143.3 1011.21   147.3 1012.05   157.2 1011.07   219.1 1008.65   223.1    1009
     237 1013.17     241 1013.75     251 1014.26     265 1013.42   270.9 1014.31
   278.9 1017.06   290.9 1023.98   300.8 1027.46   312.8 1032.58   334.8 1045.85
#Mann= 3 , 0 , 0
       0     .06       0   105.4    .045       0   127.3     .06       0
#XS Ineff= 2 , 0
                          146.61         1013.97
Permanent Ineff=
       F       F
Bank Sta=105.4,127.3
XS Rating Curve= 0 ,0
Exp/Cntr=0.3,0.1

Type RM Length L Ch R = 1 ,5799.3  ,192.1,186.7,181.1
XS GIS Cut Line= 2
     1669430.994      585318.037      1669151.48      585317.169
#Sta/Elev= 30
       0 1044.05      18 1036.18    31.9 1031.78    49.9 1023.22    69.9 1014.94
    73.9 1013.53    81.9 1011.64    83.8 1010.82    85.8 1009.59    92.7 1004.56
    93.8 1003.84    95.8 1003.05   105.8 1002.49   107.7 1002.54   111.8 1003.96
   113.8 1004.66   119.8 1005.78   125.8 1007.39   127.8 1007.65   133.8 1008.05
   167.7 1008.87   199.6 1012.55   209.6 1012.67   231.6 1012.09   251.6 1012.63
   261.6  1012.3   269.5 1011.56   275.5  1011.3   277.5 1011.35   279.5 1011.72
#Mann= 3 , 0 , 0
       0     .08       0    92.7    .045       0   111.8     .06       0
Bank Sta=92.7,111.8
XS Rating Curve= 0 ,0
Exp/Cntr=0.3,0.1

Type RM Length L Ch R = 1 ,5612.6  ,133.1,133.6,133.5
XS GIS Cut Line= 3
     1669387.591      585114.044     1669337.244      585127.065
     1669115.022      585182.621
#Sta/Elev= 30
       0 1038.87     5.8 1036.87    11.6 1036.46    17.3 1035.17      27  1030.7
    44.3 1019.92      58 1012.79      60 1011.08    67.9 1002.52    69.9 1001.15
    71.8 1000.53    75.9  1000.2    86.8 1001.21    93.8 1002.73    99.8 1005.85
   103.8  1006.2   151.6 1005.44   177.5 1002.95   191.4 1002.72   195.4 1003.25
   203.4 1006.86   209.4 1009.01   219.3 1010.94   231.3 1011.04   253.2 1010.26
   261.2 1010.49   265.1 1011.21   271.1 1013.88   273.1  1014.4   281.1 1015.47
#Mann= 3 , 0 , 0
       0      .1       0    69.9    .045       0    86.8      .1       0
#XS Ineff= 2 , 0
                          117.18         1013.67
Permanent Ineff=
       F       F
Bank Sta=69.9,86.8
XS Rating Curve= 0 ,0
Exp/Cntr=0.3,0.1

Type RM Length L Ch R = 1 ,5479    ,202.3,204.4,207.9
XS GIS Cut Line= 3
     1669332.036      584995.121     1669302.522      584998.593
     1669083.772      585051.544
#Sta/Elev= 30
       0 1033.21       4 1032.18     9.9 1029.64    15.8 1026.08    23.8 1021.76
    25.8 1020.05    31.7    1016    37.7  1010.8    45.6 1002.83    47.6 1001.18
    49.6 1000.14    51.6  999.67    57.6  999.16    66.6  999.96    71.5 1001.78
    75.5  1002.8    85.5 1004.18    89.5 1004.37   113.4 1002.88   125.3 1000.88
   135.3 1000.94   157.2  1003.6   173.1  1004.7   183.1 1007.89   189.1 1008.99
     205 1009.07   222.9 1007.92   230.9 1007.97   242.8    1010   254.8 1012.94
#Mann= 3 , 0 , 0
       0      .1       0    49.6    .045       0    66.6     .07       0
#XS Ineff= 2 , 0
                           89.35         1007.28
Permanent Ineff=
       F       F
Bank Sta=49.6,66.6
XS Rating Curve= 0 ,0
Exp/Cntr=0.3,0.1