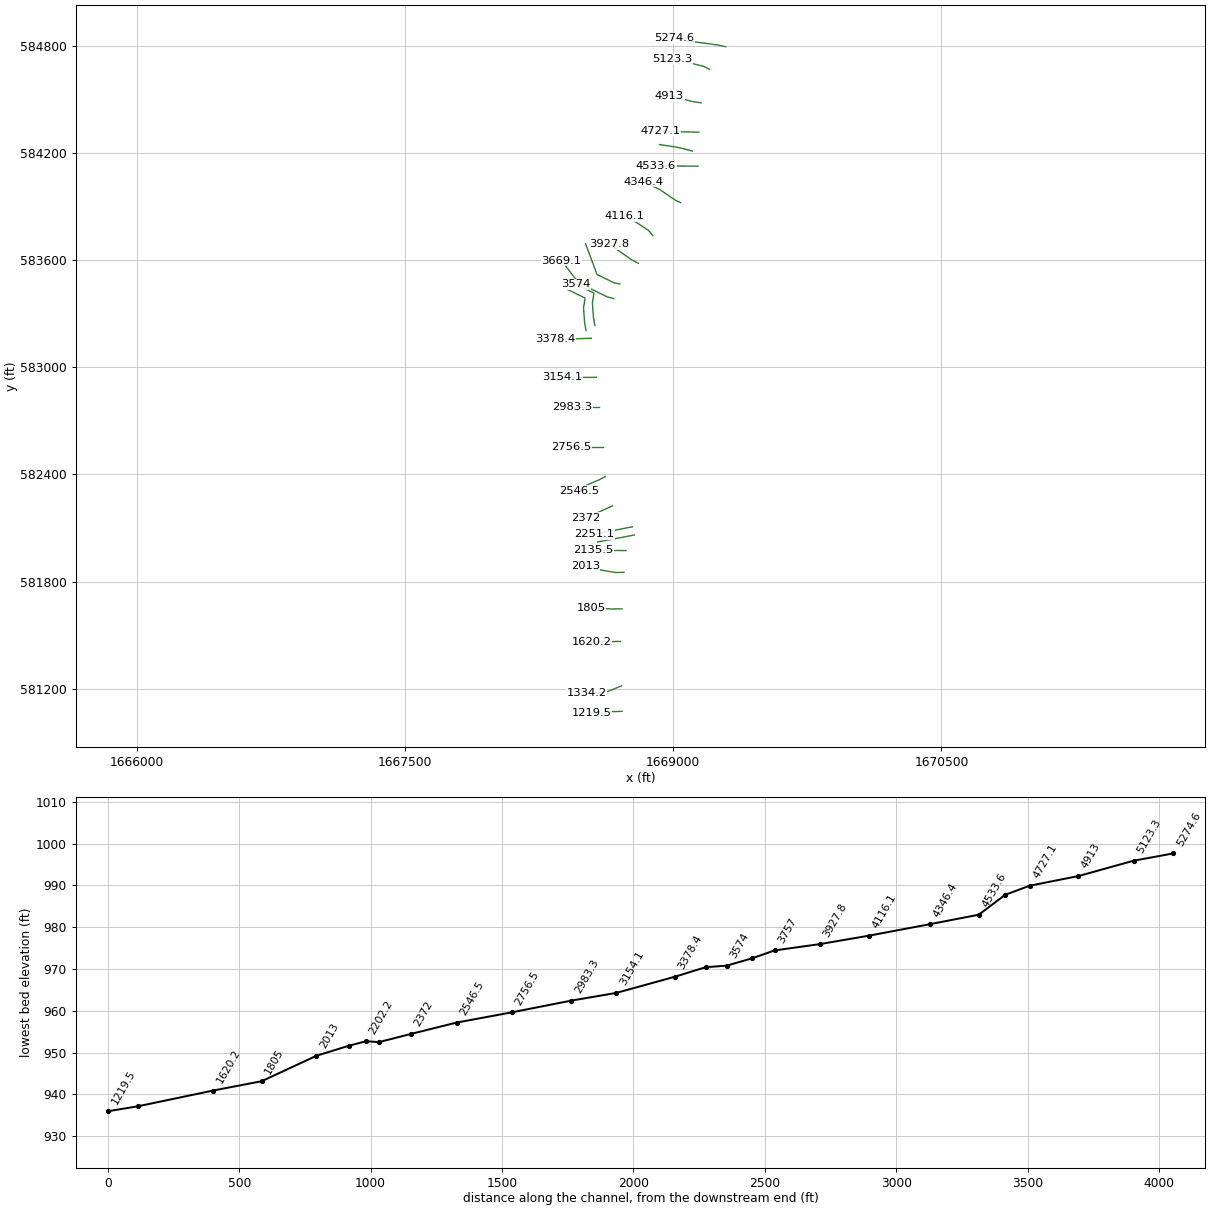
HEC-RAS study MCGRAWRUN.prj: MCGRAWRUN

--- MCGRAWRUN.g01 (geometry) --- (continued)

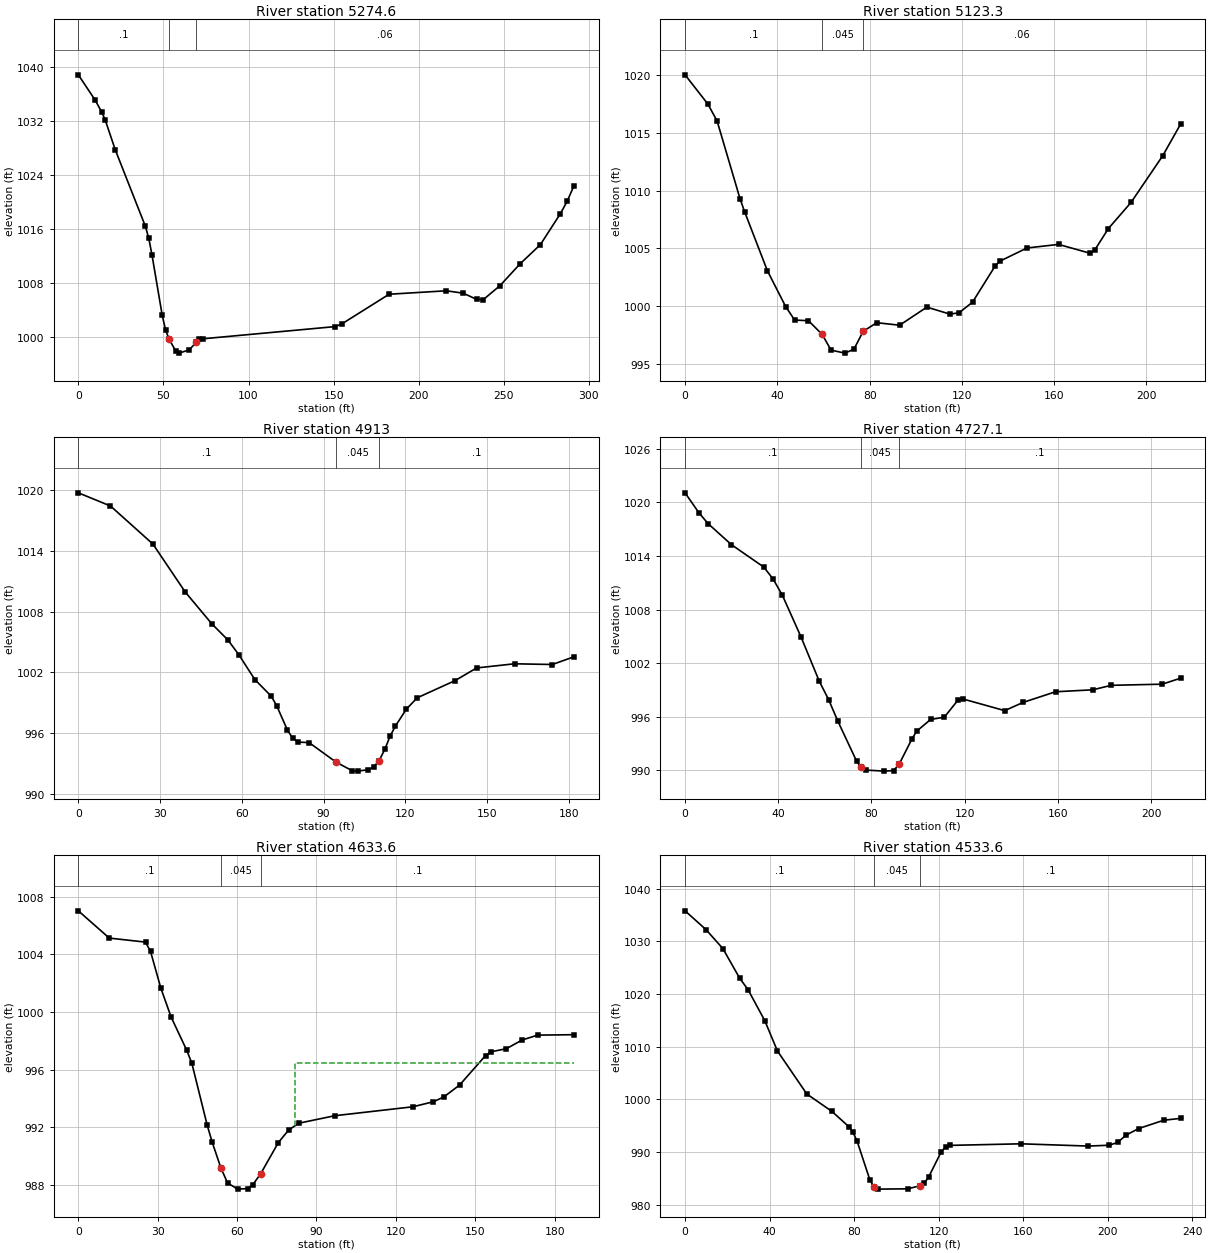
Type RM Length L Ch R = 1 ,5274.6  ,152.5,151.3,147.3
XS GIS Cut Line= 4
     1669293.841        584794.6      1669249.57      584804.148
     1669127.174      584820.641     1669006.515      584841.475
#Sta/Elev= 30
       0 1038.77     9.8 1035.07    13.8 1033.25    15.8  1032.1    21.7  1027.7
    39.4 1016.39    41.4 1014.61    43.3 1012.14    49.3 1003.23    51.3 1001.04
    53.3  999.74    57.2  997.97    59.2  997.65    65.2  998.14    69.2  999.23
    71.2   999.7    73.2  999.77   150.9 1001.57   154.8 1001.96   182.6 1006.35
   216.2 1006.86   226.1 1006.51     234  1005.6   237.9 1005.54   247.8 1007.63
   259.6 1010.85   271.5 1013.68   283.3 1018.27   287.3 1020.12   291.2 1022.37
#Mann= 3 , 0 , 0
       0      .1       0    53.3    .045       0    69.2     .06       0
Bank Sta=53.3,69.2
XS Rating Curve= 0 ,0
Exp/Cntr=0.3,0.1

Type RM Length L Ch R = 1 ,5123.3  ,210.4,210.2,209.1
XS GIS Cut Line= 4
     1669202.695      584668.732     1669168.841      584685.225
     1669069.015       584709.53     1668996.098      584724.287
#Sta/Elev= 30
       0 1020.05     9.9 1017.51    13.9 1016.04    23.8 1009.32    25.8 1008.18
    35.7 1003.05    43.6  999.95    47.5  998.78    53.5  998.72    59.4  997.54
    63.3  996.17    69.3  995.91    73.2  996.25    77.2   997.8    83.1  998.55
      93  998.33   104.8   999.9   114.7   999.3   118.7   999.4   124.6 1000.33
   134.5  1003.5   136.4 1003.88   148.2 1005.03   161.9 1005.34   175.6 1004.57
   177.6 1004.86   183.5 1006.72   193.3 1008.98     207 1013.02   214.8 1015.78
#Mann= 3 , 0 , 0
       0      .1       0    59.4    .045       0    77.2     .06       0
Bank Sta=59.4,77.2
XS Rating Curve= 0 ,0
Exp/Cntr=0.3,0.1

Type RM Length L Ch R = 1 ,4913    ,180.4,185.9,191
XS GIS Cut Line= 3
      1669155.82      584480.364     1669105.473      584488.176
     1668978.737      584521.162
#Sta/Elev= 30
       0 1019.74    11.8 1018.44    27.4 1014.67    39.2 1009.95      49 1006.79
    54.9  1005.2    58.9 1003.74    64.8 1001.28    70.8  999.64    72.8   998.7
    76.7  996.32    78.7  995.46    80.7   995.1    84.7  995.05    94.6  993.12
   100.6  992.26   102.5  992.23   106.5  992.37   108.5  992.67   110.4  993.27
   112.5  994.38   114.4  995.67   116.4  996.69   120.4  998.36   124.4  999.48
   138.3 1001.18   146.2 1002.43   160.1 1002.84     174 1002.77   181.9 1003.53
#Mann= 3 , 0 , 0
       0      .1       0    94.6    .045       0   110.4      .1       0
Bank Sta=94.6,110.4
XS Rating Curve= 0 ,0
Exp/Cntr=0.3,0.1

Type RM Length L Ch R = 1 ,4727.1  ,98.1,93.5,88.9
XS GIS Cut Line= 2
     1669143.667      584316.301     1668930.994      584320.641
#Sta/Elev= 30
       0 1021.06       6 1018.81     9.9 1017.61    19.9 1015.26    33.8 1012.75
    37.8 1011.41    41.8 1009.58    49.7 1004.98    57.6  999.98    61.6  997.93
    65.6   995.5    73.6  991.05    75.5  990.33    77.5  990.04    85.5  989.92
    89.5  989.98    91.9   990.7    97.4  993.53    99.4  994.39   105.4   995.7
   111.3  995.96   117.3  997.92   119.3  997.99   137.2  996.69   145.1  997.61
     159   998.8     175  999.02   182.9  999.52   204.8  999.65   212.7 1000.32
#Mann= 3 , 0 , 0
       0      .1       0    75.5    .045       0    91.9      .1       0
Bank Sta=75.5,91.9
XS Rating Curve= 0 ,0
Exp/Cntr=0.3,0.1

Type RM Length L Ch R = 1 ,4633.6  ,94.6,100,104.5
XS GIS Cut Line= 4
     1669106.717      584209.892     1669065.485      584221.828
     1669016.656      584232.678      1668923.34      584246.784
#Sta/Elev= 30
       0 1007.02    11.7 1005.13    25.4 1004.85    27.3  1004.2    31.2 1001.65
    35.1  999.64      41  997.34    42.9  996.45    48.7  992.16    50.6  990.97
    53.9  989.18    56.4  988.15    60.2  987.72    64.1  987.76      66  988.04
    68.9  988.78    75.6  990.95    79.5  991.82    83.3  992.29    96.9  992.81
   126.4  993.43   134.2  993.78   138.2  994.12   144.1  994.94   153.9  996.98
   155.9  997.24   161.8  997.46   167.7  998.06   173.6   998.4   187.3  998.43
#Mann= 3 , 0 , 0
       0      .1       0    53.9    .045       0    68.9      .1       0
#XS Ineff= 2 , 0
                           81.84          996.44
Permanent Ineff=
       F       F
Bank Sta=53.9,68.9
XS Rating Curve= 0 ,0
Exp/Cntr=0.3,0.1

Type RM Length L Ch R = 1 ,4533.6  ,200.3,187.2,173.3
XS GIS Cut Line= 2
     1669138.459      584126.197     1668904.084      584127.065
#Sta/Elev= 30
       0 1035.79     9.9 1032.23    17.9 1028.62    25.8 1023.03    29.8 1020.82
    37.7 1014.96    43.7 1009.19    57.6 1001.03    69.5  997.72    77.5  994.82
    79.4   993.8    81.4  992.06    87.4  984.75    89.4  983.35    91.4  982.98
   105.3  983.04   111.2  983.62   113.2  984.14   115.2  985.26   121.2  990.09
   123.2  990.98   125.1  991.28   158.9  991.58   190.7  991.15   200.6  991.31
   204.6  991.84   208.6  993.23   214.5  994.47   226.4  996.05   234.4  996.41
#Mann= 3 , 0 , 0
       0      .1       0    89.4    .045       0   111.2      .1       0
Bank Sta=89.4,111.2
XS Rating Curve= 0 ,0
Exp/Cntr=0.3,0.1

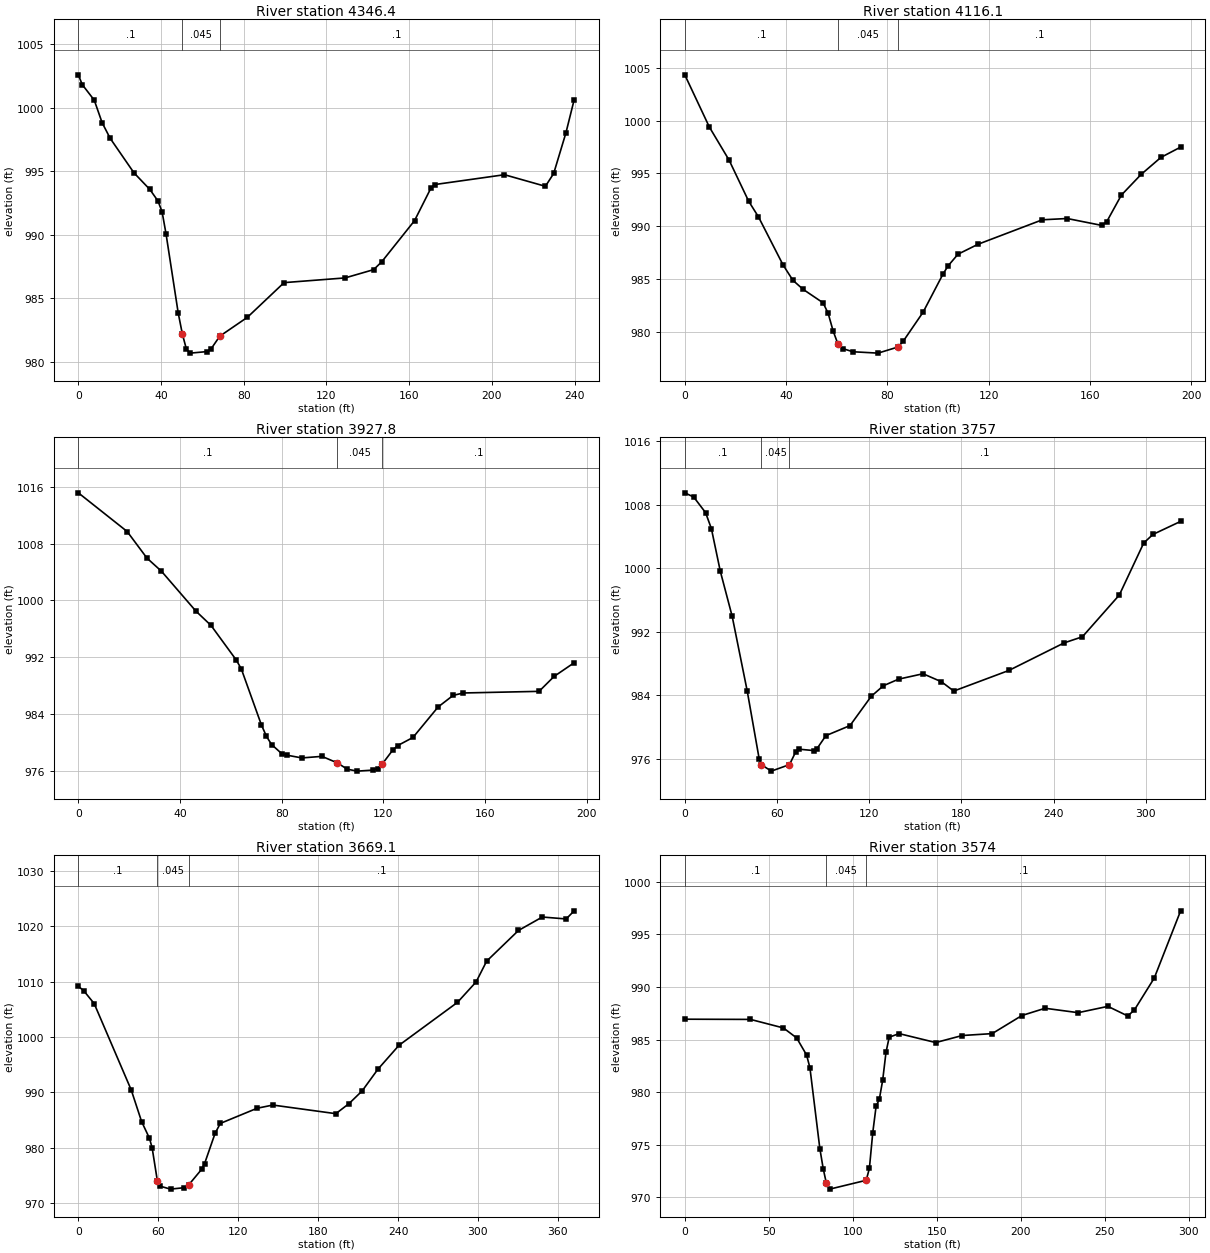
Type RM Length L Ch R = 1 ,4346.4  ,229.7,230.3,230.5
XS GIS Cut Line= 4
     1669042.105      583921.336     1669010.855      583936.093
     1668924.917      583995.121     1668833.772      584038.523
#Sta/Elev= 30
       0 1002.57     1.9  1001.8     7.7 1000.58    11.5  998.81    15.4  997.58
    26.9  994.87    34.6  993.56    38.5  992.66    40.5  991.81    42.4  990.09
    48.3  983.86    50.3  982.21    52.3  980.99    54.2   980.7    62.1  980.82
    64.1  981.01    68.4  982.03    81.8  983.52    99.5  986.24     129  986.61
   142.8  987.26   146.7  987.87   162.6  991.11   170.5  993.66   172.5  993.95
   206.1  994.72   225.9  993.81   229.9  994.82   235.8     998   239.8 1000.61
#Mann= 3 , 0 , 0
       0      .1       0    50.3    .045       0    68.4      .1       0
Bank Sta=50.3,68.4
XS Rating Curve= 0 ,0
Exp/Cntr=0.3,0.1

Type RM Length L Ch R = 1 ,4116.1  ,188.6,188.2,187.3
XS GIS Cut Line= 4
     1668886.506      583737.091     1668861.332      583766.605
     1668797.096       583809.14     1668726.784      583847.334
#Sta/Elev= 30
       0 1004.35     9.7   999.4    17.5  996.26    25.2  992.38    29.1  990.88
    38.8  986.33    42.7  984.87    46.7  984.02    54.6  982.74    56.6  981.75
    58.6  980.05    60.5  978.82    62.5  978.39    66.4   978.1    76.3  977.97
    84.2  978.55    86.2  979.08    94.1  981.85     102  985.48     104  986.25
   107.9  987.35   115.8  988.29   141.2  990.61     151  990.73   164.6  990.08
   166.6  990.42   172.4  992.95   180.2  994.91     188  996.52   195.8   997.5
#Mann= 3 , 0 , 0
       0      .1       0    60.5    .045       0    84.2      .1       0
Bank Sta=60.5,84.2
XS Rating Curve= 0 ,0
Exp/Cntr=0.3,0.1

Type RM Length L Ch R = 1 ,3927.8  ,167,170.8,174.1
XS GIS Cut Line= 3
     1668805.126      583581.926     1668766.063      583602.759
     1668642.799      583689.565
#Sta/Elev= 30
       0 1015.15    19.2  1009.7      27 1005.95    32.7  1004.1    46.2   998.5
    52.2  996.46    62.1   991.6    64.1  990.34      72  982.45      74  980.83
      76  979.69      80   978.4      82  978.19    87.9   977.8    95.8  978.02
   101.8  977.11   105.8  976.21   109.7  975.94   115.7  976.08   117.7   976.3
   119.6  976.98   123.6  978.88   125.6  979.54   131.6  980.68   141.5  984.98
   147.4  986.61   151.4  986.95   181.2  987.18   187.1  989.28     195  991.21
#Mann= 3 , 0 , 0
       0      .1       0   101.8    .045       0   119.6      .1       0
Bank Sta=101.8,119.6
XS Rating Curve= 0 ,0
Exp/Cntr=0.3,0.1

Type RM Length L Ch R = 1 ,3757    ,88,88,87.9
XS GIS Cut Line= 4
     1668701.827      583466.475     1668669.709      583472.551
     1668574.223      583519.426     1668509.987      583691.301
#Sta/Elev= 30
       0 1009.51     5.8 1008.98    13.5 1007.02    17.3    1005    23.1  999.63
    30.8  993.97    40.6  984.55    48.4  975.98    49.9  975.24    56.3  974.44
    68.1  975.26    72.1  976.84      74  977.21    83.9  977.03    85.9  977.24
    91.8  978.91   107.5  980.18   121.3  983.87   129.2   985.2   139.1  986.03
     155  986.71     167   985.7     175  984.53   210.9  987.13   246.8   990.6
   258.7  991.37   282.7  996.63   298.6 1003.19   304.6 1004.27   322.6 1005.91
#Mann= 3 , 0 , 0
       0      .1       0    49.9    .045       0    68.1      .1       0
Bank Sta=49.9,68.1
XS Rating Curve= 0 ,0
Exp/Cntr=0.3,0.1

Type RM Length L Ch R = 1 ,3669.1  ,124.2,95.1,58.3
XS GIS Cut Line= 5
     1668667.105      583384.878     1668630.647      583394.426
     1668531.688      583443.037     1668464.848      583481.232
      1668374.57      583597.551
#Sta/Elev= 30
       0 1009.17       4 1008.39    11.9 1006.05    39.7  990.44    47.5  984.72
    53.4   981.7    55.4  979.98    59.3  974.05    61.3  973.05    69.2  972.51
      79  972.76      83  973.32    92.8  976.16    94.8  977.14   102.7  982.63
   106.6  984.39   134.2  987.13     146  987.71   193.3  986.15   203.2  987.97
   213.1  990.28   224.9  994.19   240.8  998.53   284.6 1006.27   298.6 1009.97
   306.5 1013.72   330.4 1019.27   348.3  1021.7   366.2 1021.35   372.2 1022.82
#Mann= 3 , 0 , 0
       0      .1       0    59.3    .045       0      83      .1       0
Bank Sta=59.3,83
XS Rating Curve= 0 ,0
Exp/Cntr=0.3,0.1

Type RM Length L Ch R = 1 ,3574    ,81.9,80,85.3
XS GIS Cut Line= 5
      1668562.07      583233.836     1668554.258      583278.107
     1668548.181      583360.572     1668556.862      583415.259
     1668456.167      583464.739
#Sta/Elev= 30
       0  986.94    39.1  986.92    58.7  986.11    66.6  985.16    72.5  983.54
    74.5  982.32    80.4  974.65    82.4  972.74    84.3  971.34    86.3  970.79
     108  971.63   109.9  972.76   111.9  976.15   113.9  978.67   115.8  979.32
   117.8  981.13   119.8  983.81   121.7  985.23   127.6  985.57   149.4  984.72
   165.2  985.39     183  985.57   200.7  987.29   214.5  987.98   234.2  987.56
   251.9  988.16   263.7  987.25   267.6   987.8   279.5  990.85   295.2  997.24
#Mann= 3 , 0 , 0
       0      .1       0    84.3    .045       0     108      .1       0
Bank Sta=84.3,108
XS Rating Curve= 0 ,0
Exp/Cntr=0.3,0.1

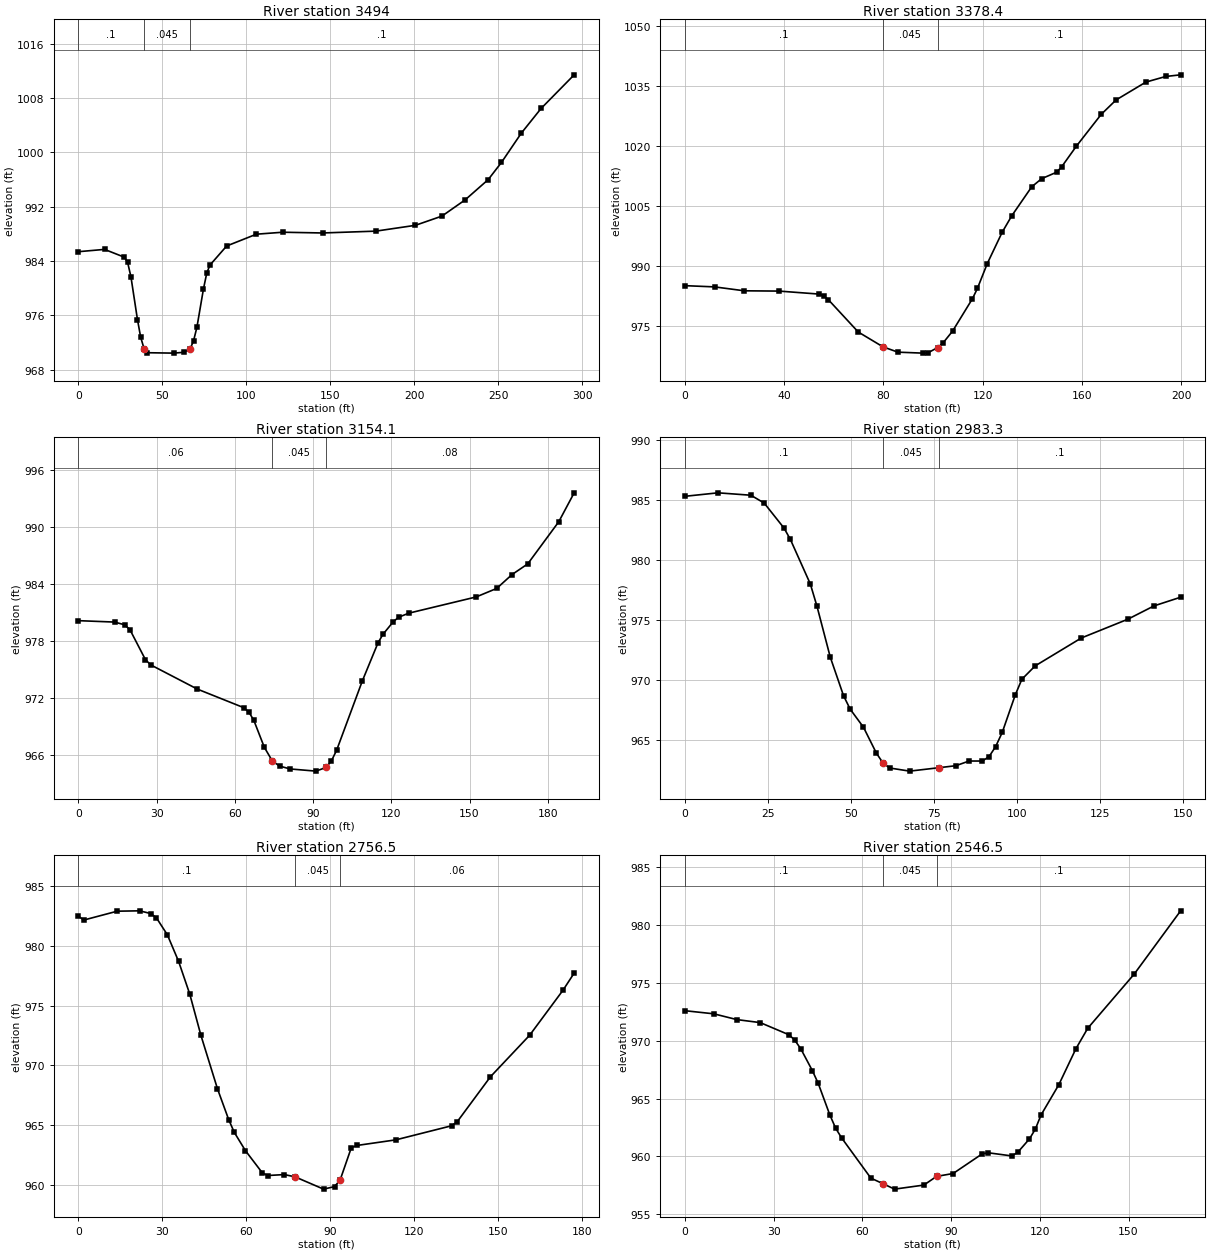
Type RM Length L Ch R = 1 ,3494    ,73.2,115.6,157.8
XS GIS Cut Line= 5
     1668512.591      583206.058     1668504.779      583250.329
     1668498.702      583332.794     1668507.383      583387.482
     1668406.688      583436.961
#Sta/Elev= 30
       0  985.37    15.6  985.71    27.4  984.56    29.3  983.84    31.3   981.7
    35.2  975.37    37.1  972.79    39.1   971.1      41  970.48    56.8  970.42
    62.7  970.54    66.6  971.06    68.6  972.24    70.6  974.23    74.5  979.89
    76.5  982.26    78.4  983.41    88.3  986.21     106  987.95   121.7  988.24
   145.4  988.13   177.1   988.4   200.7  989.26   216.5  990.62   230.3  993.01
     244  995.99   251.9  998.52   263.7 1002.83   275.5 1006.48   295.2 1011.44
#Mann= 3 , 0 , 0
       0      .1       0    39.1    .045       0    66.6      .1       0
Bank Sta=39.1,66.6
XS Rating Curve= 0 ,0
Exp/Cntr=0.3,0.1

Type RM Length L Ch R = 1 ,3378.4  ,224.9,224.3,223.3
XS GIS Cut Line= 2
     1668542.105      583162.655     1668342.452      583155.711
#Sta/Elev= 30
       0  985.04      12  984.73      24  983.75      38  983.68    53.9  982.94
    55.9  982.52    57.9  981.49    69.9  973.44    79.9  969.72    85.9   968.4
    95.9  968.16    97.9  968.21   101.9  969.56   103.9  970.59   107.9  973.66
   115.9  981.76   117.9  984.33   121.9  990.58   127.9  998.41   131.8 1002.56
   139.8 1009.77   143.8  1011.8   149.8 1013.41   151.8 1014.72   157.8 1019.94
   167.8 1027.89   173.8  1031.5   185.8 1035.96   193.8 1037.37   199.8 1037.78
#Mann= 3 , 0 , 0
       0      .1       0    79.9    .045       0   101.9      .1       0
Bank Sta=79.9,101.9
XS Rating Curve= 0 ,0
Exp/Cntr=0.3,0.1

Type RM Length L Ch R = 1 ,3154.1  ,170.9,170.8,170.4
XS GIS Cut Line= 2
     1668569.883      582943.905     1668379.779      582943.037
#Sta/Elev= 30
       0  980.15    13.9     980    17.8  979.71    19.8  979.19    25.7  976.05
    27.7  975.49    45.6  972.93    63.4  970.97    65.4   970.5    67.3  969.62
    71.3  966.79    74.4  965.33    77.2   964.8    81.2   964.5    91.1  964.27
      95  964.66      97  965.34      99  966.45   108.9   973.8   114.9  977.81
   116.8  978.71   120.8  980.05   122.8  980.51   126.7  980.94   152.5  982.65
   160.4  983.55   166.3  985.02   172.3  986.14   184.2  990.59   190.1  993.64
#Mann= 3 , 0 , 0
       0     .06       0    74.4    .045       0      95     .08       0
Bank Sta=74.4,95
XS Rating Curve= 0 ,0
Exp/Cntr=0.3,0.1

Type RM Length L Ch R = 1 ,2983.3  ,226,226.8,226.3
XS GIS Cut Line= 2
     1668582.904      582778.975     1668433.598      582778.975
#Sta/Elev= 30
       0  985.28      10  985.57    19.9  985.37    23.9  984.72    29.9  982.63
    31.8  981.69    37.8  977.99    39.8  976.14    43.8  971.91    47.8   968.7
    49.8  967.58    53.8  966.08    57.7  963.92    59.7   963.1    61.7  962.69
    67.7  962.43    76.4  962.71    81.6  962.88    85.6  963.27    89.6  963.27
    91.6  963.63    93.6  964.47    95.6  965.66    99.5  968.76   101.5  970.07
   105.5  971.18   119.4   973.5   133.4  975.06   141.3  976.17   149.3  976.89
#Mann= 3 , 0 , 0
       0      .1       0    59.7    .045       0    76.4      .1       0
Bank Sta=59.7,76.4
XS Rating Curve= 0 ,0
Exp/Cntr=0.3,0.1

Type RM Length L Ch R = 1 ,2756.5  ,197.7,210,219.7
XS GIS Cut Line= 2
     1668605.473      582555.884      1668428.39      582555.884
#Sta/Elev= 30
       0   982.5       2  982.18    13.9  982.92    21.9  982.95    25.9  982.72
    27.9  982.36    31.8  980.94    35.8  978.72    39.8  975.97    43.8   972.5
    49.7  968.03    53.7  965.45    55.7  964.38    59.7  962.84    65.7  960.99
    67.6  960.76    73.6  960.84    77.4  960.65    87.6  959.62    91.5  959.83
    93.5  960.38    97.5  963.09    99.5  963.28   113.4  963.75   133.3  964.93
   135.3  965.26   147.2  969.04   161.2  972.52   173.1  976.29   177.1  977.73
#Mann= 3 , 0 , 0
       0      .1       0    77.4    .045       0    93.5     .06       0
Bank Sta=77.4,93.5
XS Rating Curve= 0 ,0
Exp/Cntr=0.3,0.1

Type RM Length L Ch R = 1 ,2546.5  ,176.1,174.5,173.3
XS GIS Cut Line= 4
      1668620.23       582388.35     1668582.036      582368.384
     1668509.119      582337.134     1668473.529      582309.357
#Sta/Elev= 30
       0  972.59     9.8  972.32    17.6  971.82    25.5  971.56    35.3   970.5
    37.2  970.03    39.2   969.3    43.1  967.42    45.1  966.31      49   963.6
      51  962.43      53   961.6    62.9  958.12    66.9  957.65    70.9  957.17
    80.8  957.52    85.1  958.27    90.7  958.52   100.6  960.23   102.6  960.31
   110.5  960.04   112.5  960.34   116.5  961.51   118.5  962.36   120.4  963.57
   126.4  966.18   132.2   969.3   136.2  971.07   151.9  975.75   167.6  981.22
#Mann= 3 , 0 , 0
       0      .1       0    66.9    .045       0    85.1      .1       0
Bank Sta=66.9,85.1
XS Rating Curve= 0 ,0
Exp/Cntr=0.3,0.1

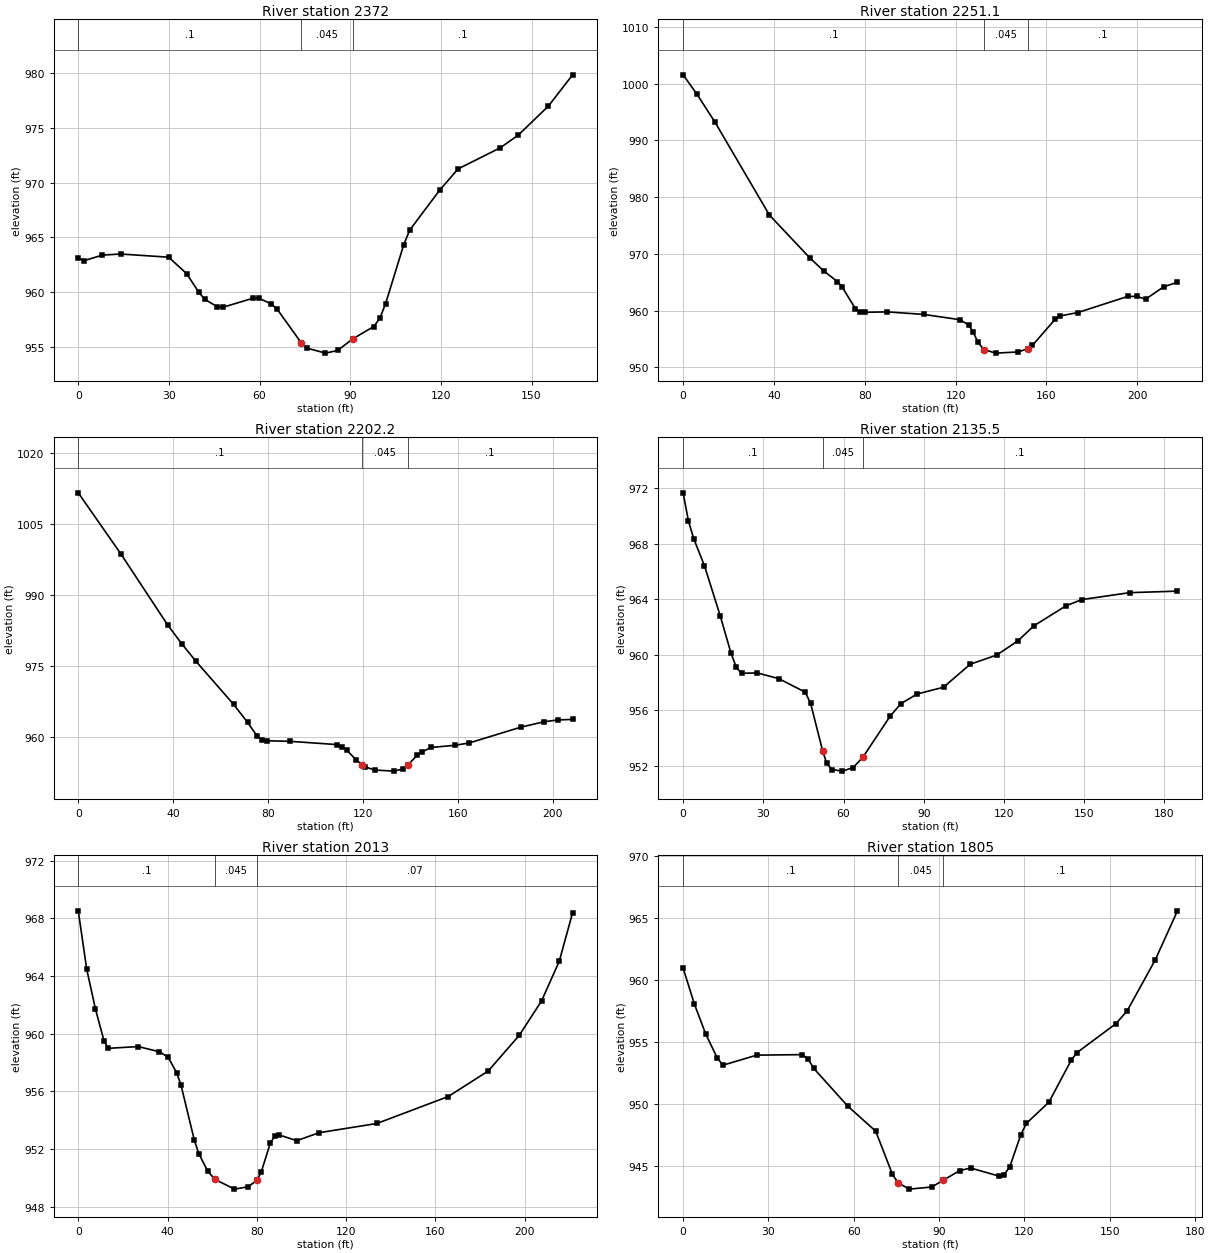
Type RM Length L Ch R = 1 ,2372    ,126.2,120.9,115.5
XS GIS Cut Line= 2
     1668661.029      582224.287     1668511.723      582157.447
#Sta/Elev= 30
       0  963.11       2  962.89       8  963.39      14  963.49    29.9   963.2
    35.9  961.69    39.9  959.99    41.9  959.35    45.9  958.69    47.9  958.63
    57.8  959.45    59.8  959.45    63.8  958.94    65.8  958.46    73.8  955.38
    75.8  954.89    81.8  954.44    85.8  954.68    90.9  955.75    97.8  956.87
    99.8  957.62   101.7  958.95   107.7  964.33   109.7  965.68   119.7  969.35
   125.7  971.26   139.6  973.18   145.6  974.34   155.6     977   163.6  979.85
#Mann= 3 , 0 , 0
       0      .1       0    73.8    .045       0    90.9      .1       0
Bank Sta=73.8,90.9
XS Rating Curve= 0 ,0
Exp/Cntr=0.3,0.1

Type RM Length L Ch R = 1 ,2251.1  ,48.8,48.9,48.7
XS GIS Cut Line= 2
     1668771.431      582107.027      1668557.73      582065.433
#Sta/Elev= 30
       0 1001.57       6  998.21      14  993.25      38  976.85    55.9  969.25
    61.9  967.01    67.9  965.12    69.9  964.24    75.9  960.33    77.9   959.8
    79.9   959.7    89.9  959.77   105.9  959.33   121.8   958.4   125.8  957.47
   127.8  956.16   129.8  954.46   132.5   953.1   137.8   952.5   147.5  952.71
   151.8  953.28   153.8  953.85   163.8  958.45   165.8  959.04   173.8  959.65
   195.7  962.49   199.7  962.51   203.7  962.02   211.7  964.21   217.7  964.99
#Mann= 3 , 0 , 0
       0      .1       0   132.5    .045       0   151.8      .1       0
Bank Sta=132.5,151.8
XS Rating Curve= 0 ,0
Exp/Cntr=0.3,0.1

Type RM Length L Ch R = 1 ,2202.2  ,70.6,66.7,62.1
XS GIS Cut Line= 2
     1668782.281      582061.454     1668577.695       582022.03
#Sta/Elev= 30
       0 1011.65    17.9  998.76    37.7  983.66    43.6   979.7    49.6  975.98
    65.5  966.84    71.4  963.02    75.4  960.14    77.4  959.35    79.4  959.14
    89.3  959.02   109.1  958.33   111.1  957.92   113.1  957.19   117.1  955.12
   119.6   954.1     121   953.6     125  952.94     133  952.71   136.9  953.16
   138.9  953.96   142.9  956.09   144.8  956.76   148.8  957.72   158.7  958.18
   164.7  958.66   186.5  962.01   196.4  963.17   202.4  963.56   208.4  963.66
#Mann= 3 , 0 , 0
       0      .1       0   119.6    .045       0   138.9      .1       0
Bank Sta=119.6,138.9
XS Rating Curve= 0 ,0
Exp/Cntr=0.3,0.1

Type RM Length L Ch R = 1 ,2135.5  ,125.6,122.4,118.5
XS GIS Cut Line= 2
     1668736.549      581974.287     1668551.654      581975.155
#Sta/Elev= 30
       0  971.68       2  969.64       4  968.36       8  966.41    13.9   962.8
    17.9  960.13    19.9  959.09    21.9  958.67    27.8  958.69    35.8  958.28
    45.7   957.3    47.7  956.49    52.2  953.06    53.7  952.18    55.7  951.72
    59.6  951.61    63.6  951.87    67.2   952.6    77.5  955.59    81.5  956.48
    87.5  957.17    97.4  957.66   107.4  959.32   117.3  959.98   125.2     961
   131.2  962.09   143.2  963.53   149.1  963.98     167  964.48   184.9  964.59
#Mann= 3 , 0 , 0
       0      .1       0    52.2    .045       0    67.2      .1       0
Bank Sta=52.2,67.2
XS Rating Curve= 0 ,0
Exp/Cntr=0.3,0.1

Type RM Length L Ch R = 1 ,2013    ,206.3,208,209.4
XS GIS Cut Line= 4
     1668725.265      581852.759     1668679.258      581851.023
     1668561.202      581870.989     1668508.251       581888.35
#Sta/Elev= 30
       0  968.52     3.8  964.46     7.7  961.72    11.5  959.53    13.4  958.99
    26.9  959.11    36.4  958.75    40.3  958.37    44.1  957.29      46  956.46
      52  952.63      54  951.69      58  950.48    61.2  949.91      70  949.23
      76  949.39      80  949.83      82  950.42      86   952.4      88   952.9
    89.9  952.99    97.9  952.59   107.9  953.14   133.8  953.78   165.8  955.65
   183.7  957.42   197.6  959.89   207.6  962.28   215.5  965.02   221.5  968.39
#Mann= 3 , 0 , 0
       0      .1       0    61.2    .045       0      80     .07       0
Bank Sta=61.2,80
XS Rating Curve= 0 ,0
Exp/Cntr=0.3,0.1

Type RM Length L Ch R = 1 ,1805    ,182.3,184.9,187.3
XS GIS Cut Line= 4
     1668713.922      581648.043     1668652.073      581646.958
       1668593.5      581652.455     1668540.369      581651.371
#Sta/Elev= 30
       0  960.95       4  958.03       8  955.61      12  953.72      14  953.13
    25.9  953.94    41.9  953.98    43.9  953.65    45.9  952.88    57.9  949.83
    67.7  947.82    73.6  944.34    75.6  943.66    79.5  943.15    87.4  943.32
    91.5  943.87    97.2  944.64   101.1  944.85   110.9  944.21   112.8  944.31
   114.8  944.92   118.7  947.51   120.7  948.45   128.6  950.15   136.4  953.51
   138.4  954.13   152.2  956.48   156.1   957.5     166  961.61   173.8  965.56
#Mann= 3 , 0 , 0
       0      .1       0    75.6    .045       0    91.5      .1       0
Bank Sta=75.6,91.5
XS Rating Curve= 0 ,0
Exp/Cntr=0.3,0.1

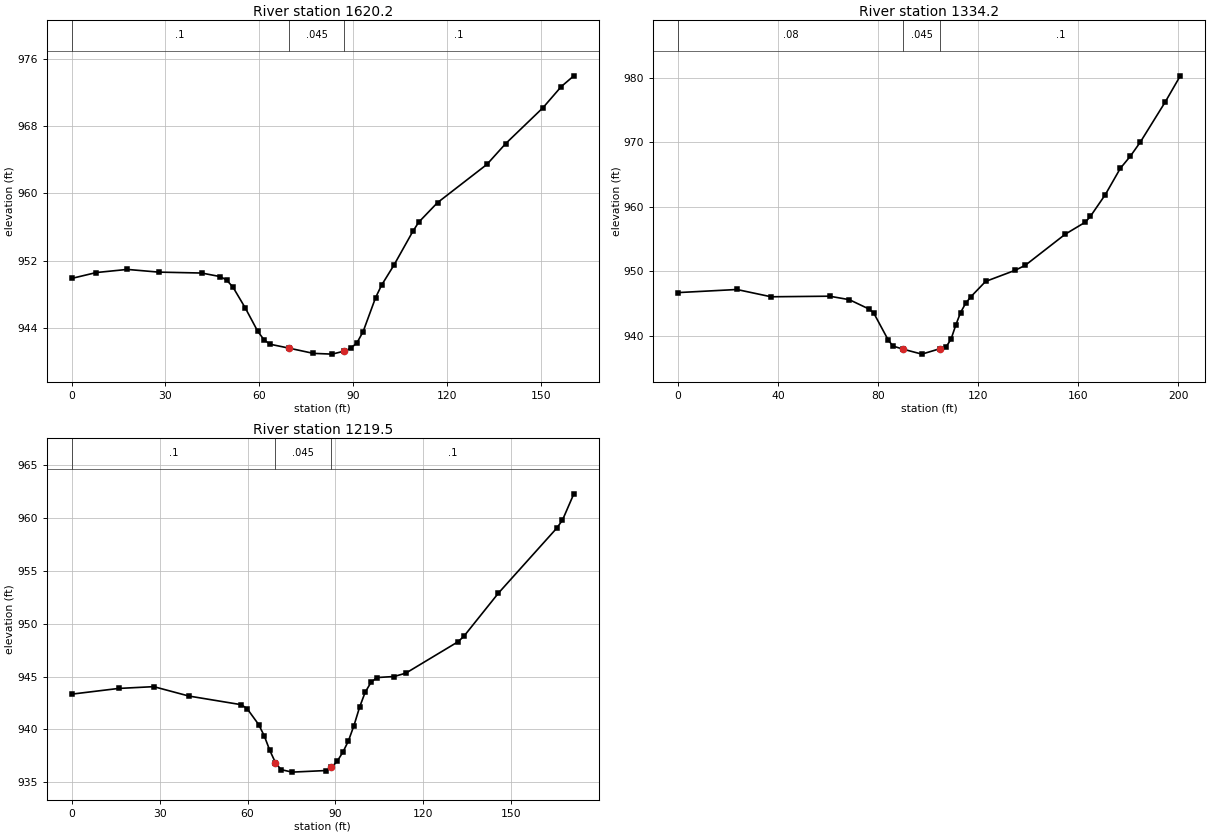
Type RM Length L Ch R = 1 ,1620.2  ,279.1,285.9,290.2
XS GIS Cut Line= 2
     1668704.431      581465.607     1668543.841      581463.003
#Sta/Elev= 30
       0   949.9     7.9   950.6    17.8  950.97    27.8  950.65    41.6  950.54
    47.6  950.11    49.6  949.69    51.6  948.86    55.5  946.41    59.5  943.63
    61.5  942.62    63.4  942.09    69.4  941.63    77.3     941    83.3  940.91
    87.2  941.27    89.2   941.6    91.2  942.23    93.2  943.57    97.2  947.62
    99.1  949.09   103.1   951.5   109.1  955.48     111  956.58     117   958.9
   132.8  963.44   138.8  965.91   150.7  970.16   156.6  972.69   160.6  973.96
#Mann= 3 , 0 , 0
       0      .1       0    69.4    .045       0    87.2      .1       0
Bank Sta=69.4,87.2
XS Rating Curve= 0 ,0
Exp/Cntr=0.3,0.1

Type RM Length L Ch R = 1 ,1334.2  ,117.1,114.7,114.9
XS GIS Cut Line= 4
     1668710.508      581216.475     1668643.667      581188.697
     1668602.869      581176.544     1668516.931      581177.412
#Sta/Elev= 30
       0   946.7    23.5  947.18    37.2  946.05    60.6  946.14    68.5   945.6
    76.2  944.18    78.2  943.57      84  939.38    85.9  938.41    89.9  937.93
    97.5  937.15   104.9  938.01   107.2  938.26   109.2  939.49   111.1  941.68
     113  943.61     115  945.01     117  946.01     123  948.43   134.9  950.17
   138.9  950.94   154.9  955.77   162.9  957.63   164.9  958.51   170.9   961.9
   176.9  965.98   180.9  967.86   184.9  970.05   194.9   976.3   200.9  980.34
#Mann= 3 , 0 , 0
       0     .08       0    89.9    .045       0   104.9      .1       0
Bank Sta=89.9,104.9
XS Rating Curve= 0 ,0
Exp/Cntr=0.3,0.1

Type RM Length L Ch R = 1 ,1219.5  ,73.3,70.5,66.3
XS GIS Cut Line= 4
      1668713.98      581074.114     1668654.084      581072.378
     1668615.022      581062.829     1668543.841      581063.697
#Sta/Elev= 30
       0  943.34      16  943.88      28  944.05      40  943.16    57.9  942.34
    59.9  941.95    63.8  940.46    65.7  939.39    67.6  938.01    69.5  936.87
    71.4   936.2    75.2  935.96    86.7  936.11    88.6   936.4    90.6     937
    92.5  937.84    94.4  938.91    96.3  940.37    98.2  942.09   100.1  943.51
   102.1  944.45   104.1  944.91     110  945.01     114  945.33   131.8   948.3
   133.8  948.82   145.6  952.91   165.4  959.03   167.4   959.8   171.3   962.3
#Mann= 3 , 0 , 0
       0      .1       0    69.5    .045       0    88.6      .1       0
Bank Sta=69.5,88.6
XS Rating Curve= 0 ,0
Exp/Cntr=0.3,0.1