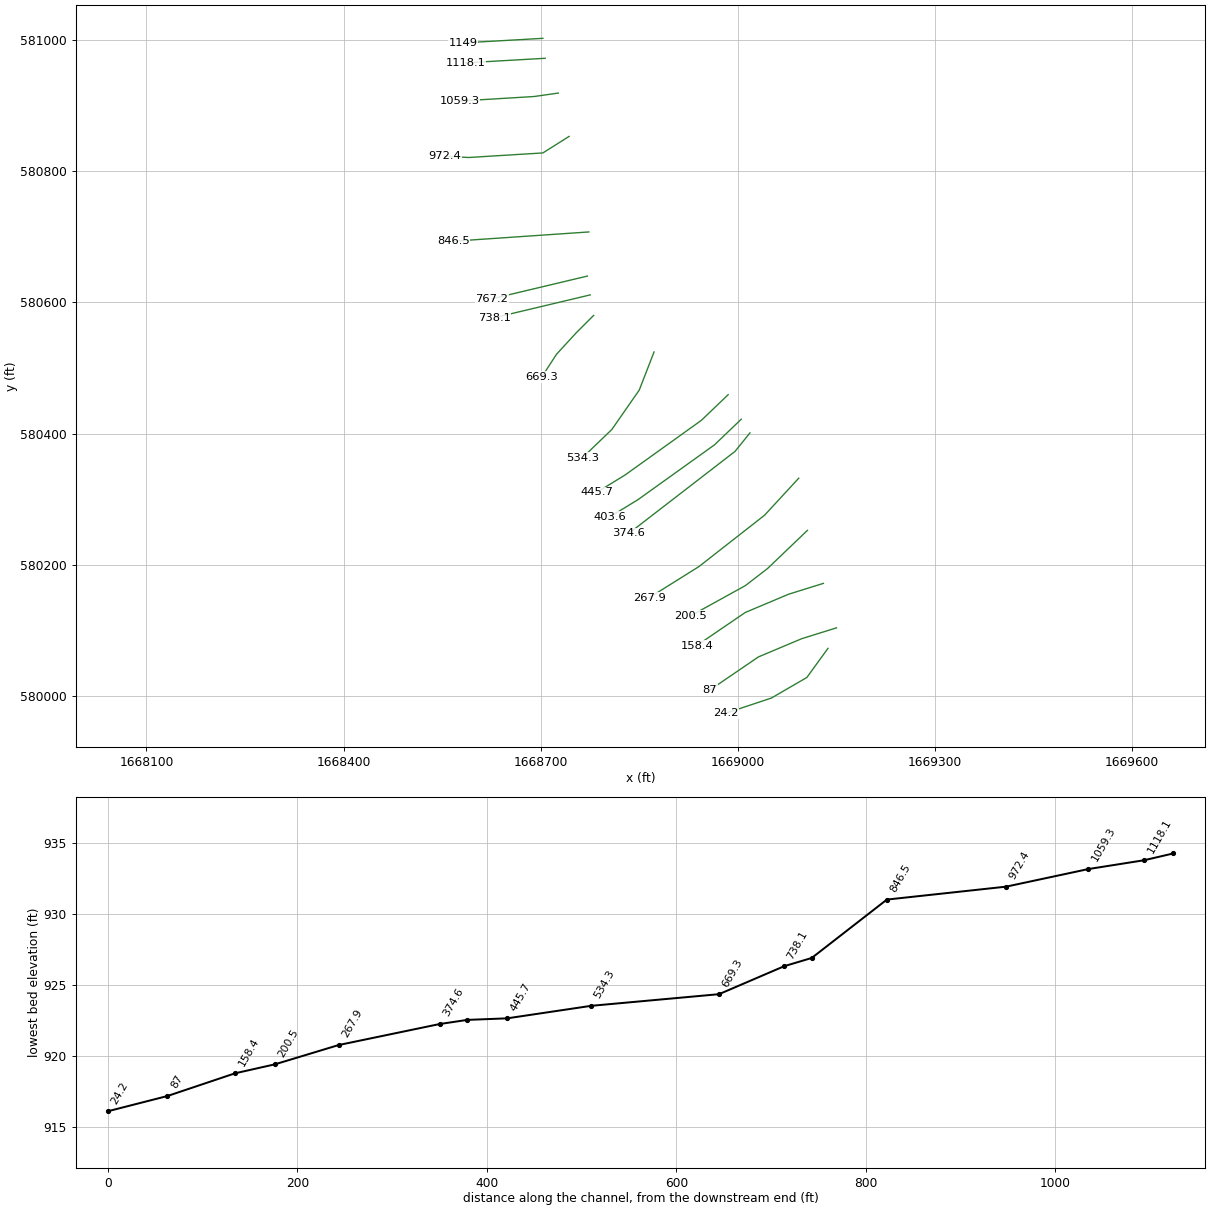
HEC-RAS study MCGRAWRUN.prj: MCGRAWRUN

--- MCGRAWRUN.g01 (geometry) --- (continued)

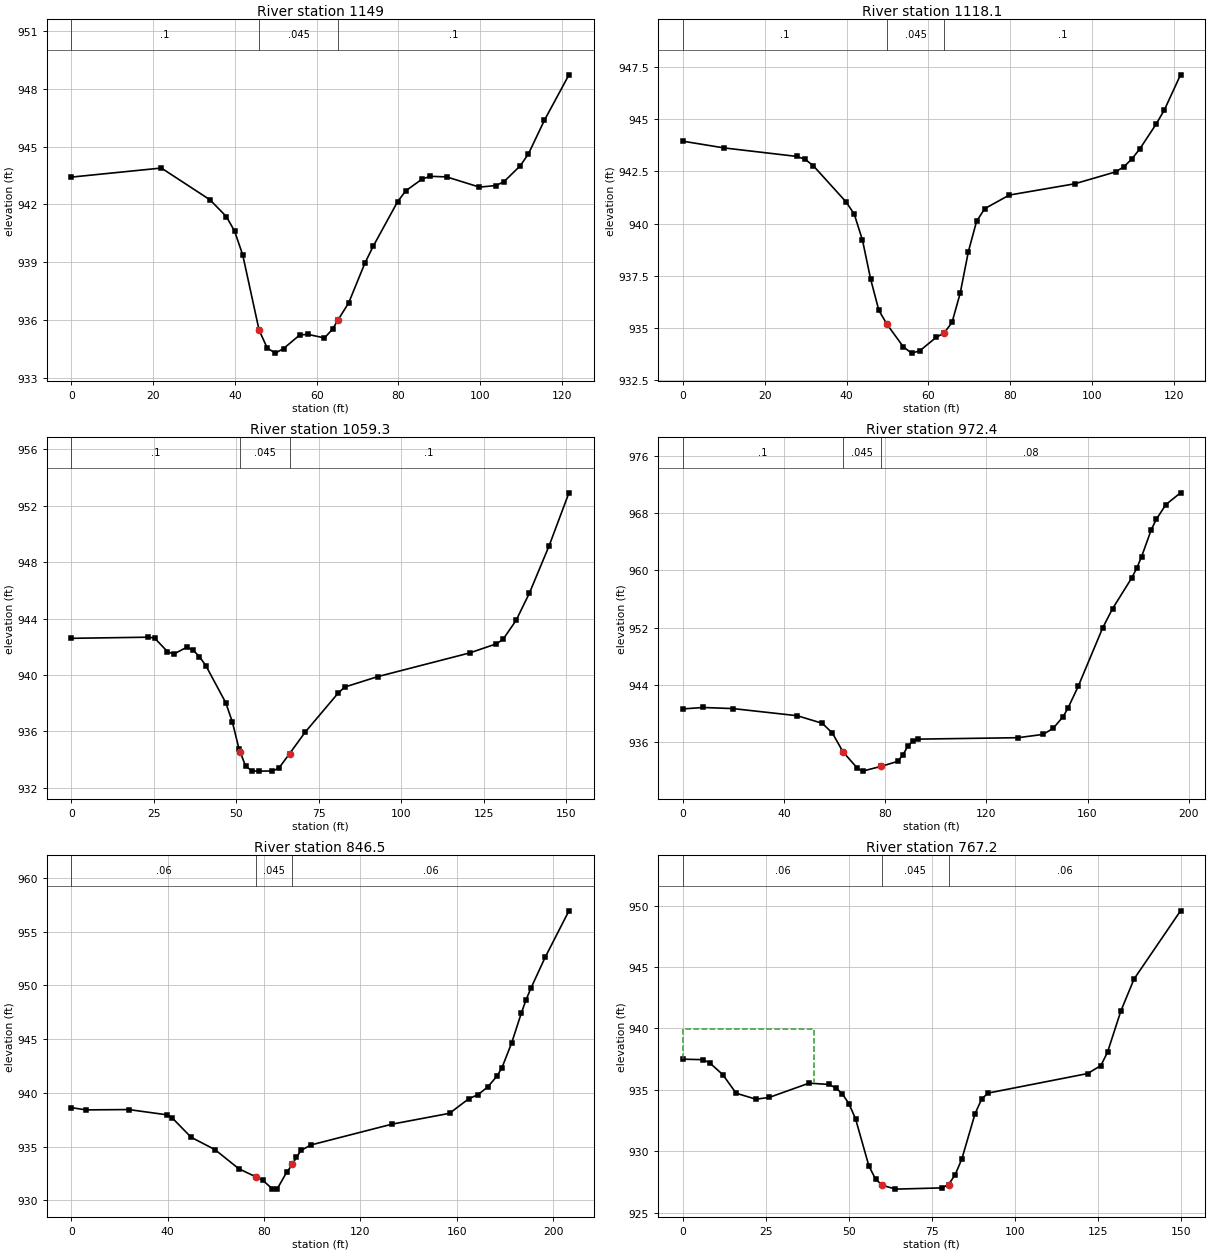
Type RM Length L Ch R = 1 ,1149    ,31.1,30.9,31.1
XS GIS Cut Line= 2
     1668703.563      581002.065     1668582.036      580995.121
#Sta/Elev= 30
       0  943.42      22  943.89    33.9  942.24    37.9  941.37    39.9  940.62
    41.9  939.38    45.9  935.48    47.9  934.54    49.9  934.28    51.9  934.52
    55.9  935.23    57.9  935.25    61.9  935.07    63.9  935.53    65.2     936
    67.8  936.88    71.8  938.96    73.8  939.82    79.8  942.15    81.8  942.71
    85.8  943.32    87.8  943.46    91.8  943.43    99.8   942.9   103.8  942.98
   105.8  943.18   109.8  944.01   111.8  944.63   115.7  946.37   121.7  948.73
#Mann= 3 , 0 , 0
       0      .1       0    45.9    .045       0    65.2      .1       0
Bank Sta=45.9,65.2
XS Rating Curve= 0 ,0
Exp/Cntr=0.3,0.1

Type RM Length L Ch R = 1 ,1118.1  ,58.2,58.8,58.4
XS GIS Cut Line= 2
     1668707.036      580971.683     1668585.508      580964.739
#Sta/Elev= 30
       0  943.95      10  943.63    27.9  943.22    29.9  943.08    31.9  942.77
    39.9  941.04    41.9  940.45    43.9  939.21    45.9  937.34    47.9  935.85
    49.9  935.18    53.9   934.1    55.9   933.8    57.9  933.91    61.9  934.55
    63.9  934.77    65.8  935.27    67.8  936.67    69.8  938.66    71.8  940.11
    73.8  940.72    79.8  941.37    95.8  941.91   105.8  942.48   107.8  942.72
   109.8   943.1   111.8   943.6   115.7  944.76   117.7  945.43   121.7  947.13
#Mann= 3 , 0 , 0
       0      .1       0    49.9    .045       0    63.9      .1       0
Bank Sta=49.9,63.9
XS Rating Curve= 0 ,0
Exp/Cntr=0.3,0.1

Type RM Length L Ch R = 1 ,1059.3  ,86.9,86.9,87
XS GIS Cut Line= 3
     1668727.001      580918.732     1668690.542      580913.523
     1668576.827      580906.579
#Sta/Elev= 30
       0   942.6    23.3  942.68    25.2  942.62    29.1  941.66      31  941.48
    34.9  941.96    36.8  941.78    38.8   941.3    40.8  940.64    46.8  938.02
    48.8  936.65    50.8  934.75    51.1  934.57    52.8  933.53    54.8  933.19
    56.8  933.18    60.8  933.19    62.8  933.37    66.1  934.41    70.8  935.93
    80.8   938.7    82.8  939.14    92.8  939.88   120.8  941.57   128.8  942.21
   130.8  942.52   134.8  943.88   138.8   945.8   144.8  949.17   150.8  952.92
#Mann= 3 , 0 , 0
       0      .1       0    51.1    .045       0    66.1      .1       0
Bank Sta=51.1,66.1
XS Rating Curve= 0 ,0
Exp/Cntr=0.3,0.1

Type RM Length L Ch R = 1 ,972.4   ,125.6,125.9,125.9
XS GIS Cut Line= 4
     1668743.494      580852.759     1668703.563      580827.586
     1668590.716      580820.641     1668554.258      580822.378
#Sta/Elev= 30
       0  940.63     7.9  940.83    19.7  940.68    45.2  939.68    55.1  938.62
    59.1  937.25    63.3  934.62      69  932.34      71  931.94    78.3   932.6
    84.9   933.3    86.9  934.17    88.9  935.39    90.8  936.12    92.8  936.41
   132.5  936.61   142.4  937.07   146.4  937.91   150.4  939.57   152.3  940.76
   156.3  943.77     166  951.95   169.9  954.63   177.6  958.99   179.5  960.32
   181.4  961.91   185.2  965.65   187.2  967.11     191  969.18   196.8  970.82
#Mann= 3 , 0 , 0
       0      .1       0    63.3    .045       0    78.3     .08       0
Bank Sta=63.3,78.3
XS Rating Curve= 0 ,0
Exp/Cntr=0.3,0.1

Type RM Length L Ch R = 1 ,846.5   ,75.1,79.3,82.6
XS GIS Cut Line= 2
     1668773.601      580707.288     1668567.438      580693.182
#Sta/Elev= 30
       0  938.62       6  938.41    23.8  938.44    39.7  937.95    41.7   937.7
    49.7  935.86    59.6  934.71    69.5  932.93    76.8  932.15    79.5  931.84
    83.4  931.07    85.4  931.03    89.4  932.61    91.8  933.33    93.4     934
    95.4  934.64    99.4  935.14   133.1  937.08     157  938.09   164.9  939.43
   168.9  939.84   172.9  940.55   176.8  941.58   178.8  942.35   182.8  944.64
   186.8  947.41   188.8  948.67   190.8  949.74   196.7  952.61   206.6  956.95
#Mann= 3 , 0 , 0
       0     .06       0    76.8    .045       0    91.8     .06       0
Bank Sta=76.8,91.8
XS Rating Curve= 0 ,0
Exp/Cntr=0.3,0.1

Type RM Length L Ch R = 1 ,767.2   ,29.1,29.1,29.1
XS GIS Cut Line= 2
     1668771.272      580640.086     1668625.438      580605.364
#Sta/Elev= 30
       0   937.5       6  937.46       8  937.21      12  936.24      16  934.73
      22  934.24      26  934.39      38  935.55      44  935.44      46  935.17
      48  934.68      50  933.87      52  932.63      56  928.81      58  927.74
      60  927.24      64  926.92      78  927.02      80  927.29      82  928.09
      84  929.37      88  933.07      90  934.26    91.9  934.74   121.9  936.33
   125.9  936.98   127.9  938.07   131.9  941.41   135.9  944.03   149.9  949.58
#Mann= 3 , 0 , 0
       0     .06       0      60    .045       0      80     .06       0
#XS Ineff= 2 , 0
           39.54  939.99
Permanent Ineff=
       F       F
Bank Sta=60,80
XS Rating Curve= 0 ,0
Exp/Cntr=0.3,0.1

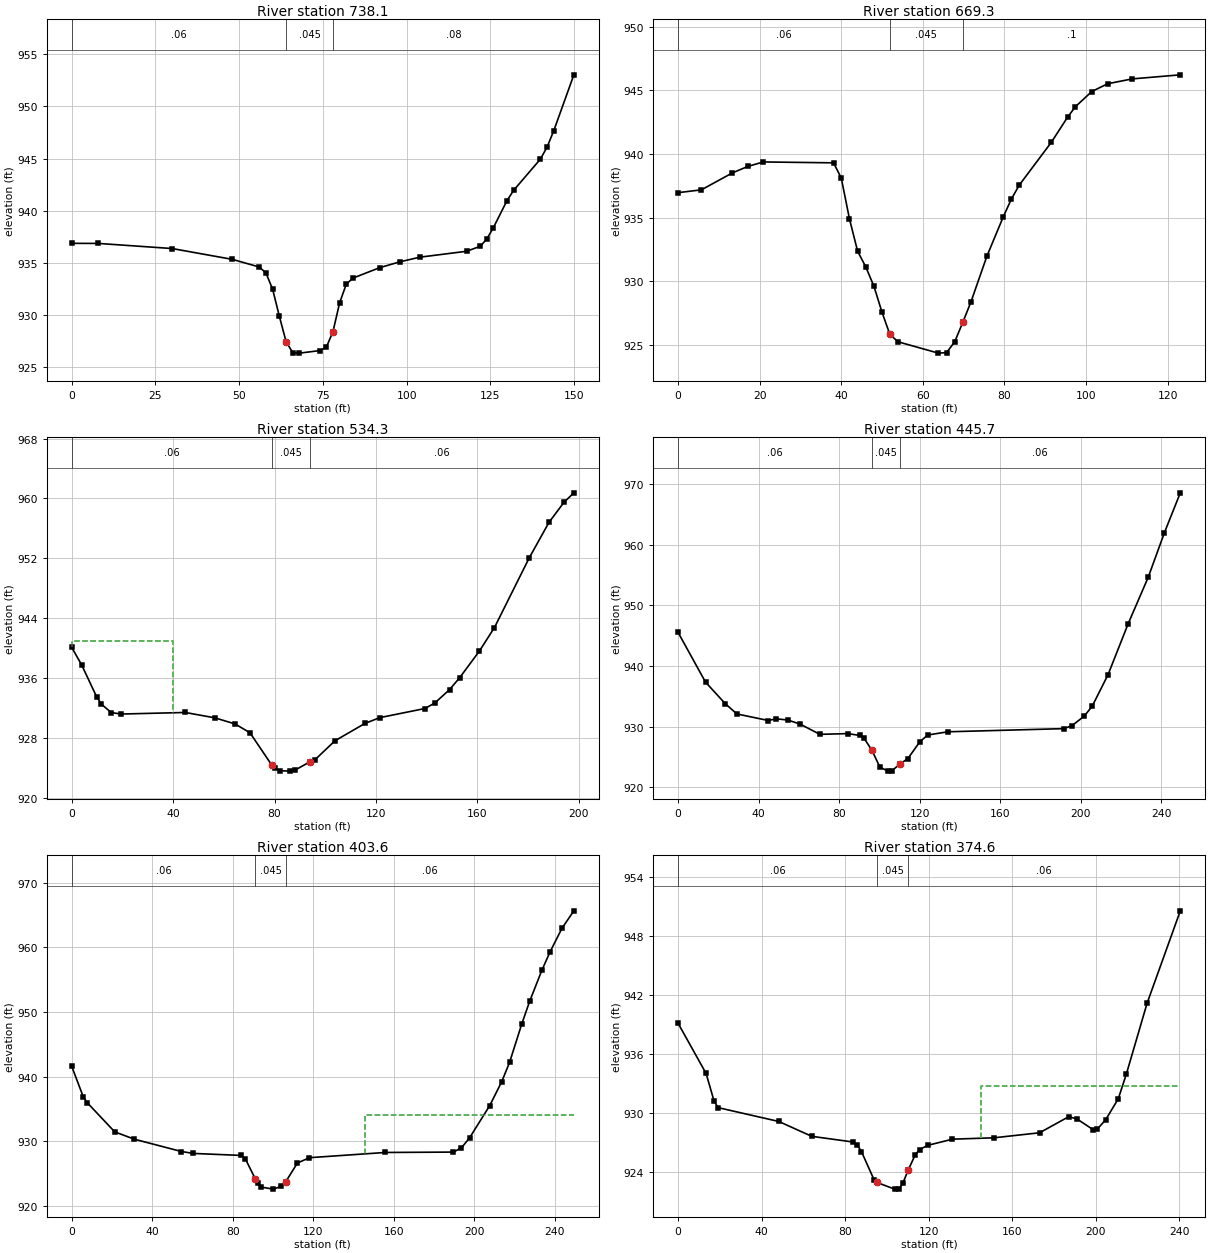
Type RM Length L Ch R = 1 ,738.1   ,55.4,68.8,83
XS GIS Cut Line= 2
     1668775.612       580611.44     1668629.779      580576.718
#Sta/Elev= 30
       0  936.87       8  936.86      30  936.37      48  935.33      56   934.6
      58  934.03      60  932.46      62  929.87      64  927.45      66  926.38
      68  926.34      74  926.58      76  926.89      78   928.4      80  931.18
      82  932.97      84  933.54    91.9  934.53    97.9  935.09   103.9  935.54
   117.9  936.11   121.9  936.58   123.9  937.27   125.9  938.38   129.9  940.94
   131.9  941.94   139.9  944.94   141.9  946.09   143.9  947.66   149.9  953.03
#Mann= 3 , 0 , 0
       0     .06       0      64    .045       0      78     .08       0
Bank Sta=64,78
XS Rating Curve= 0 ,0
Exp/Cntr=0.3,0.1

Type RM Length L Ch R = 1 ,669.3   ,131.7,135,137.2
XS GIS Cut Line= 4
      1668780.82       580580.19     1668753.911       580553.28
     1668724.397      580521.162     1668701.827       580486.44
#Sta/Elev= 30
       0  936.97     5.7  937.19    13.3  938.52    17.1  939.03    20.9  939.38
    38.1  939.31      40  938.11      42  934.91      44  932.37      46  931.14
      48  929.62      50  927.56    51.9  925.84    53.9  925.26    63.8  924.37
    65.8  924.41    67.8  925.26    69.8   926.8    71.8  928.41    75.7  931.99
    79.7  935.07    81.7  936.47    83.6  937.55    91.5  940.93    95.5  942.91
    97.4  943.72   101.4  944.91   105.3  945.52   111.3   945.9   123.1  946.22
#Mann= 3 , 0 , 0
       0     .06       0    51.9    .045       0    69.8      .1       0
Bank Sta=51.9,69.8
XS Rating Curve= 0 ,0
Exp/Cntr=0.3,0.1

Type RM Length L Ch R = 1 ,534.3   ,96.3,88.6,80.7
XS GIS Cut Line= 4
     1668872.834      580524.634     1668850.265      580466.475
     1668808.598      580406.579     1668763.459      580363.176
#Sta/Elev= 30
       0   940.1     3.9  937.78     9.8  933.52    11.7  932.51    15.6  931.38
    19.5  931.18    44.8  931.39    56.5  930.67    64.4  929.86    70.3  928.68
    78.8  924.41    80.1  923.92    82.1  923.61      86  923.55      88  923.67
    93.8  924.77    95.9  925.06   103.8   927.6   115.6  929.92   121.5   930.7
   139.3  931.92   143.2  932.66     149  934.45     153  936.04   160.8  939.62
   166.7  942.74   180.4  952.05   188.2   956.8   194.1  959.48     198  960.75
#Mann= 3 , 0 , 0
       0     .06       0    78.8    .045       0    93.8     .06       0
#XS Ineff= 2 , 0
           40.04  941.01
Permanent Ineff=
       F       F
Bank Sta=78.8,93.8
XS Rating Curve= 0 ,0
Exp/Cntr=0.3,0.1

Type RM Length L Ch R = 1 ,445.7   ,42,42.1,42.1
XS GIS Cut Line= 4
     1668985.681       580459.53     1668944.883      580420.468
     1668828.563      580337.134     1668786.029      580311.093
#Sta/Elev= 30
       0  945.54    13.6  937.36    23.4   933.8    29.2   932.1    44.8  931.02
    48.7   931.3    54.5   931.1    60.5  930.44    70.4  928.74    84.3  928.86
    90.3  928.55    92.3  928.11    96.2  926.14   100.2  923.33   104.2  922.67
   106.2  922.74   110.3  923.88   114.1  924.74   120.1  927.54     124  928.63
     134  929.16   191.6  929.68   195.6  930.17   201.6  931.72   205.6  933.35
   213.5  938.57   223.5  946.98   233.5  954.68   241.5     962   249.4  968.58
#Mann= 3 , 0 , 0
       0     .06       0    96.2    .045       0   110.3     .06       0
Bank Sta=96.2,110.3
XS Rating Curve= 0 ,0
Exp/Cntr=0.3,0.1

Type RM Length L Ch R = 1 ,403.6   ,28.1,29.1,29.7
XS GIS Cut Line= 4
     1669005.647      580422.204     1668964.848      580383.141
     1668848.529      580299.808     1668805.994      580273.766
#Sta/Elev= 30
       0  941.61     5.8  936.84     7.8  935.93    21.4  931.43    31.2  930.29
    54.5  928.39    60.5  928.09    84.3  927.78    86.3  927.23    91.3  924.08
    92.3  923.44    94.2  922.87   100.2  922.56   104.2     923   106.3  923.69
   112.1   926.6   118.1  927.43   155.8  928.24   189.6   928.3   193.6  928.97
   197.6   930.5   207.6  935.49   213.5  939.15   217.5  942.21   223.5  948.12
   227.5   951.7   233.5  956.45   237.5  959.27   243.5  962.97   249.4  965.68
#Mann= 3 , 0 , 0
       0     .06       0    91.3    .045       0   106.3     .06       0
#XS Ineff= 2 , 0
                          145.58          933.97
Permanent Ineff=
       F       F
Bank Sta=91.3,106.3
XS Rating Curve= 0 ,0
Exp/Cntr=0.3,0.1

Type RM Length L Ch R = 1 ,374.6   ,106.3,106.7,106.6
XS GIS Cut Line= 3
     1669018.827      580401.298      1668996.04      580373.086
     1668834.365      580248.303
#Sta/Elev= 30
       0  939.13    13.4  934.03    17.2  931.24    19.1  930.56    48.2  929.15
      64  927.64    83.8  927.06    85.8  926.76    87.8  926.09    93.8  923.24
    95.2  922.95   103.7  922.27   105.7  922.29   107.6  922.85   110.2  924.22
   113.6  925.78   115.6  926.28   119.5  926.72   131.4  927.35   151.3  927.49
   173.1     928     187  929.63   190.9  929.42   198.9   928.3   200.8  928.38
   204.8  929.34   210.8  931.46   214.7     934   224.6  941.18   240.5  950.57
#Mann= 3 , 0 , 0
       0     .06       0    95.2    .045       0   110.2     .06       0
#XS Ineff= 2 , 0
                          145.28           932.8
Permanent Ineff=
       F       F
Bank Sta=95.2,110.2
XS Rating Curve= 0 ,0
Exp/Cntr=0.3,0.1

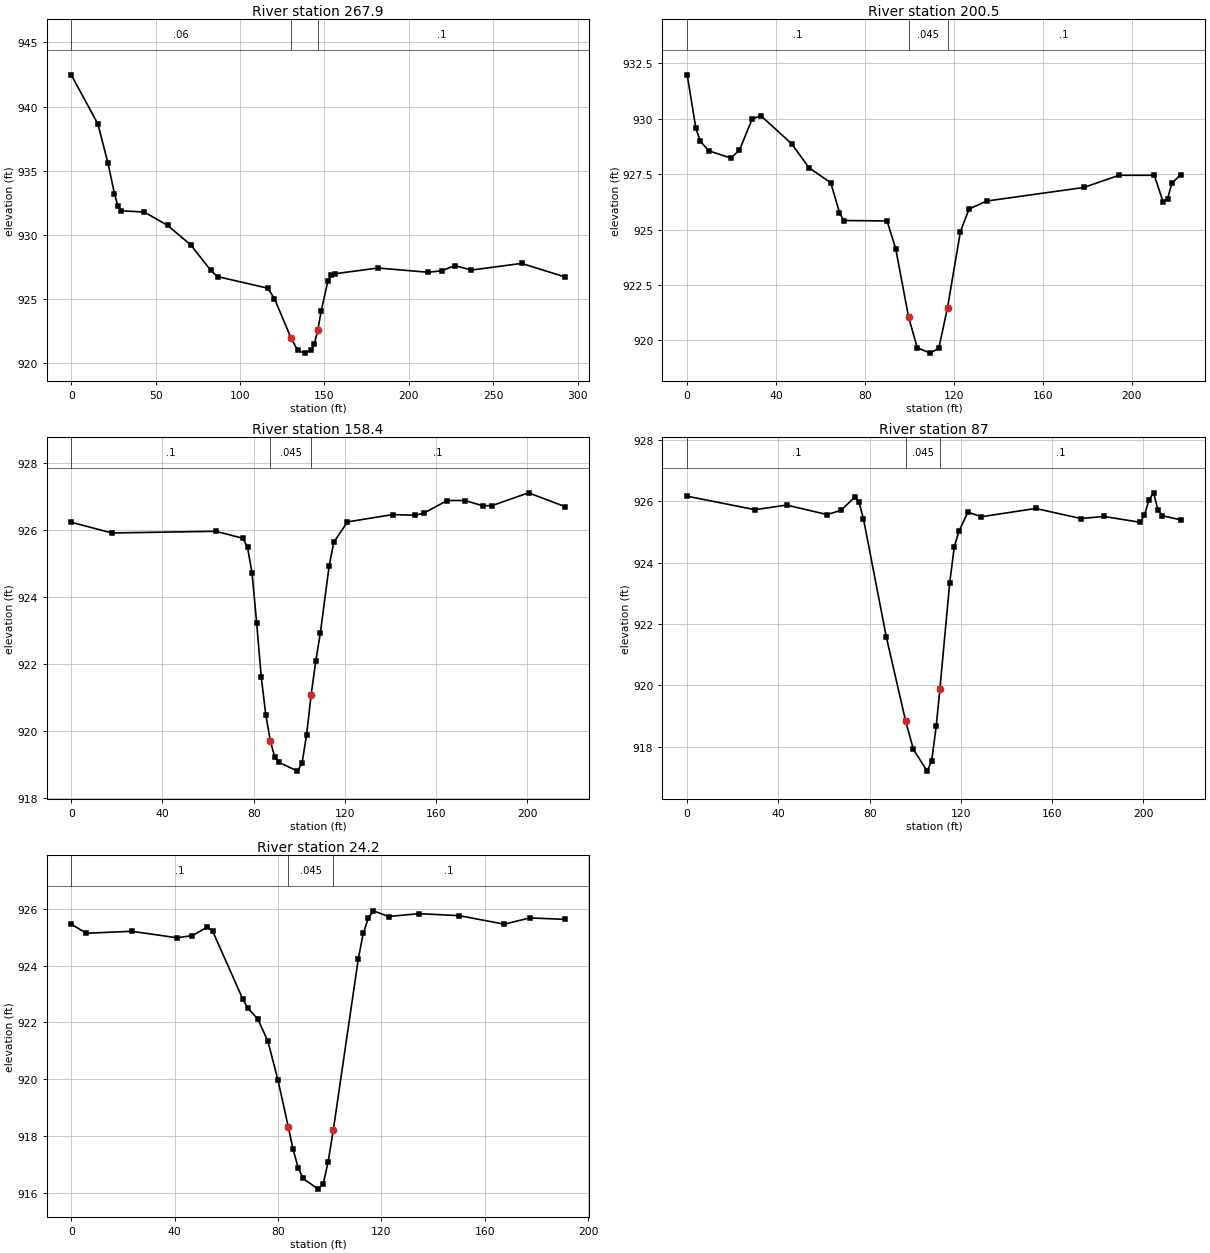
Type RM Length L Ch R = 1 ,267.9   ,67.8,67.4,66.4
XS GIS Cut Line= 4
     1669093.103       580332.36      1669041.02      580275.937
     1668941.194      580197.812     1668865.832      580150.647
#Sta/Elev= 30
       0  942.47    15.8  938.64    21.7  935.63    25.6  933.22    27.6  932.26
    29.5  931.88    43.3  931.78    57.1  930.74    70.9  929.21    82.7  927.23
    86.7  926.75   116.4  925.85   120.4  925.04   130.3  921.94   134.2     921
   138.2  920.79   142.2     921   144.1  921.54   146.1   922.6   148.1  924.08
     152  926.37     154  926.84     156  926.97   181.8  927.42   211.4  927.09
   219.4   927.2   227.3  927.61   237.1  927.26   266.8  927.78   292.4  926.73
#Mann= 3 , 0 , 0
       0     .06       0   130.3    .045       0   146.1      .1       0
Bank Sta=130.3,146.1
XS Rating Curve= 0 ,0
Exp/Cntr=0.3,0.1

Type RM Length L Ch R = 1 ,200.5   ,47.8,42,37.1
XS GIS Cut Line= 4
     1669106.341      580252.933     1669045.577      580194.773
     1669011.723      580168.732      1668928.39      580122.725
#Sta/Elev= 30
       0  931.98     3.9  929.58     5.9  928.98     9.8  928.55    19.6  928.23
    23.5  928.58    29.3     930    33.2  930.13      47  928.87    54.8  927.79
    64.6  927.11    68.5  925.77    70.4  925.41    89.9  925.39    93.8  924.14
    99.6  921.05   103.5  919.67   109.4  919.43   113.2  919.66   117.1  921.48
   122.9  924.91   126.8  925.93   134.8  926.29   178.4   926.9   194.2  927.45
   210.1  927.45   214.1  926.24   216.1   926.4     218  927.09     222  927.48
#Mann= 3 , 0 , 0
       0      .1       0    99.6    .045       0   117.1      .1       0
Bank Sta=99.6,117.1
XS Rating Curve= 0 ,0
Exp/Cntr=0.3,0.1

Type RM Length L Ch R = 1 ,158.4   ,71.3,71.4,71.4
XS GIS Cut Line= 4
     1669130.647      580172.204     1669077.695      580155.711
     1669011.723      580127.933     1668937.938      580077.586
#Sta/Elev= 30
       0  926.24    17.8  925.92    63.4  925.97    75.3  925.76    77.3  925.49
    79.3  924.71    81.3  923.24    83.3  921.62    85.3  920.49    87.3   919.7
    89.3  919.21    91.2  919.06    99.2   918.8   101.2  919.04   103.2  919.89
   105.2  921.09   107.2  922.08   109.2  922.92   113.1  924.94   115.1  925.64
   121.1  926.25   140.9  926.47   150.9  926.45   154.8  926.52   164.8  926.89
   172.7  926.89   180.6  926.73   184.6  926.74   200.5  927.12   216.4  926.71
#Mann= 3 , 0 , 0
       0      .1       0    87.3    .045       0   105.2      .1       0
Bank Sta=87.3,105.2
XS Rating Curve= 0 ,0
Exp/Cntr=0.3,0.1

Type RM Length L Ch R = 1 ,87      ,59.8,62.8,65.8
XS GIS Cut Line= 4
     1669150.612      580104.496     1669097.661      580088.003
     1669031.688      580060.225     1668957.904      580009.878
#Sta/Elev= 30
       0  926.17    29.7  925.73    43.6  925.88    61.4  925.57    67.4  925.71
    73.4  926.13    75.3  925.99    77.3  925.43    87.3  921.58    95.8  918.83
    99.2  917.91   105.2   917.2   107.2  917.53   109.2  918.67   110.8  919.87
   115.1  923.34   117.1  924.51   119.1  925.02   123.1  925.65     129   925.5
   152.8  925.77   172.7  925.44   182.6  925.51   198.5  925.32   200.5  925.55
   202.5  926.06   204.5  926.28   206.4  925.72   208.4  925.53   216.4   925.4
#Mann= 3 , 0 , 0
       0      .1       0    95.8    .045       0   110.8      .1       0
Bank Sta=95.8,110.8
XS Rating Curve= 0 ,0
Exp/Cntr=0.3,0.1

Type RM Length L Ch R = 1 ,24.2    ,31.4,24.2,17.1
XS GIS Cut Line= 4
     1669137.591      580073.246     1669105.473      580028.975
     1669051.654      579997.725     1668981.341      579974.287
#Sta/Elev= 30
       0  925.46     5.9  925.14    23.4  925.21      41  924.98    46.9  925.06
    52.7  925.36    54.7  925.22    66.4  922.82    68.3  922.51    72.2  922.12
    76.1  921.34      80  919.97      84  918.32    85.8  917.55    87.8  916.89
    89.7  916.51    95.5  916.13    97.5  916.31    99.4  917.08   101.4   918.2
   111.1  924.24     113  925.14     115  925.68   116.9  925.93   122.8  925.73
   134.5  925.83   150.1  925.76   167.6  925.46   177.4  925.68     191  925.63
#Mann= 3 , 0 , 0
       0      .1       0      84    .045       0   101.4      .1       0
Bank Sta=84,101.4
XS Rating Curve= 0 ,0
Exp/Cntr=0.3,0.1

Chan Stop Cuts=-1
Use User Specified Reach Order=0
Composite Channel Slope=5